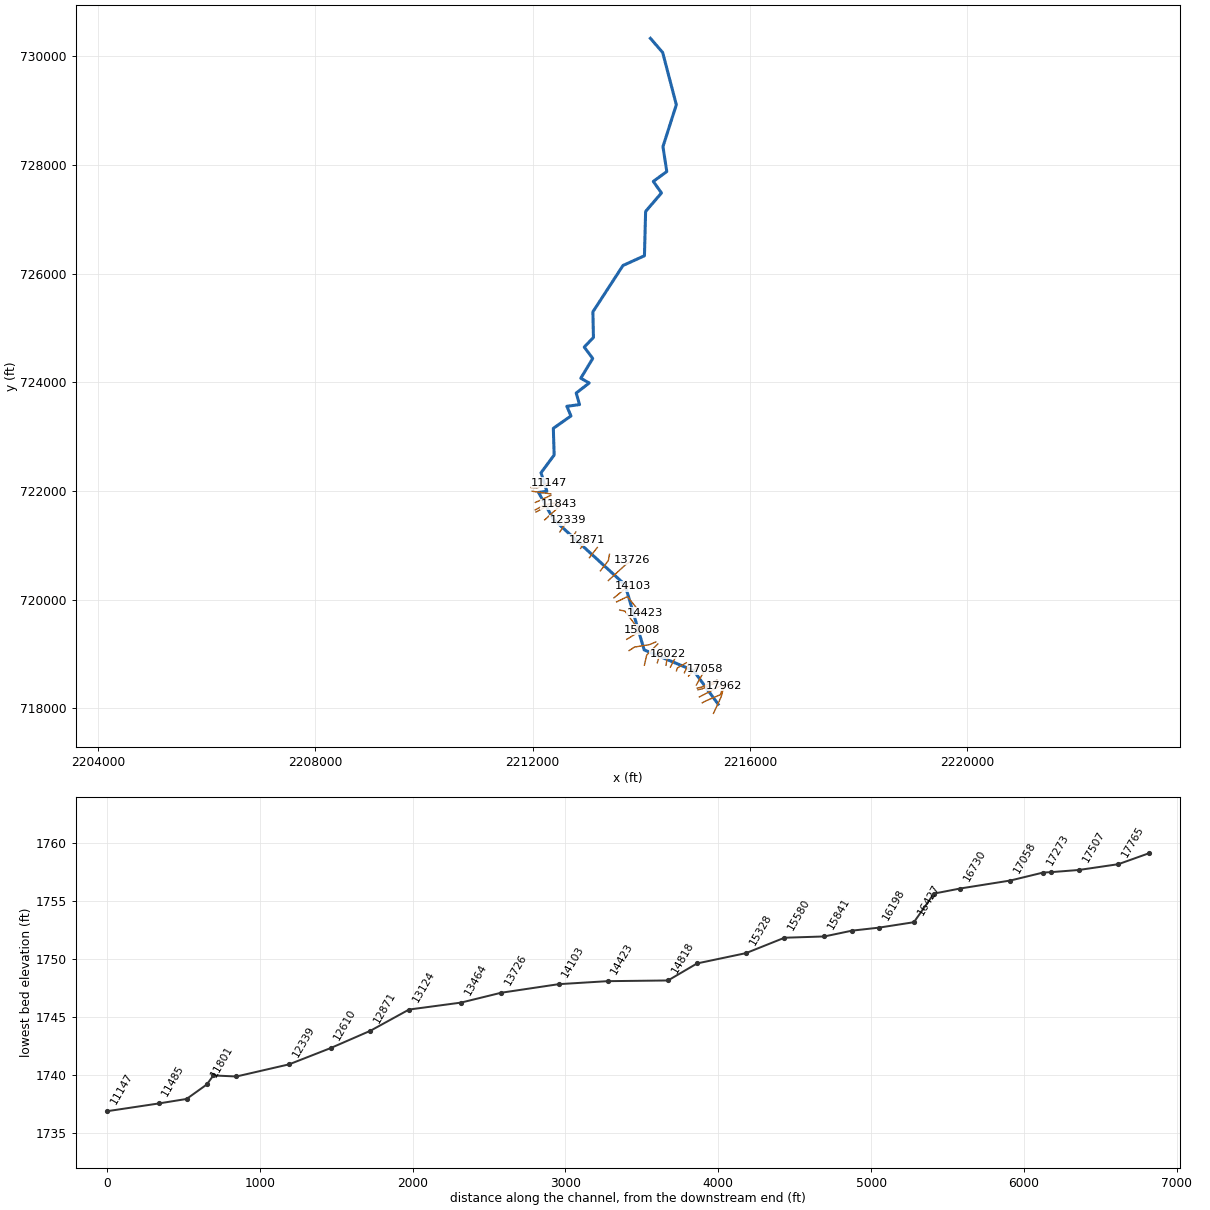
--- LILAURELFK.prj (project) ---

Proj Title=LILAURELFK
Current Plan=p01
Default Exp/Contr=0,0
English Units
Geom File=g01
Flow File=f01
Plan File=p01
BEGIN DESCRIPTION:
---------- MODELED AS PART OF WVEMD CTP PROGRAM, 2023----------
Stream Name: Little Laurel Fork
Flood Zone:  AFH
Upshur County, WV
HEC-RAS Version: RAS 6.3
Vertical Datum: NAVD88
Projection: NAD 1983 StatePlane West Virginia S FIPS 4702 (US Feet)
Terrain: 1-meter LIDAR (FEMA Region III 3DEP collected 2016-2018)
Land Use: 2019 NLCD
Hydrologic Method:
WV SIR2010-5033 regression equations
Additional Model Notes:
Main stem is LAUFSANDRN
END DESCRIPTION:
DSS Export Rating Curves= 0
DSS Export Rating Curve Sorted= 0
DSS Export Volume Flow Curves= 0
DXF OffsetX= 0
DXF OffsetY= 0
DXF ScaleX= 0
DXF ScaleY= 0

--- LILAURELFK.p01 (plan) ---

Plan Title=Floodplain
Program Version=6.31
Short Identifier=Floodplain
Geom File=g01
Flow File=f01
Subcritical Flow
K Sum by GR= 0
Std Step Tol= 0.01
Critical Tol= 0.01
Num of Std Step Trials= 20
Max Error Tol= 0.3
Flow Tol Ratio= 0.001
Split Flow NTrial= 30
Split Flow Tol= 0.02
Split Flow Ratio= 0.02
Log Output Level= 0
Friction Slope Method= 1
Unsteady Friction Slope Method= 2
Unsteady Bridges Friction Slope Method= 1
Parabolic Critical Depth
Global Vel Dist= 0 , 0 , 0
Global Log Level= 0
CheckData=True
Encroach Param=-1 ,0,0, 0
Mapping Interval=1HOUR
Computation Time Step Use Courant=        0
Computation Time Step Use Time Series=    0
Computation Time Step Count To Double=0
Computation Time Step Max Doubling=0
Computation Time Step Max Halving=0
Computation Time Step Residence Courant=0
Run HTab= 0
Run UNet= 0
Run Sediment= 0
Run PostProcess= 0
Run WQNet= 0
Run RASMapper=-1
UNET Theta= 0
UNET Theta Warmup= 0
UNET ZTol= 0
UNET ZSATol= 0
UNET MxIter= 0
UNET Max Iter WO Improvement= 0
UNET MaxInSteps= 0
UNET DtIC= 0
UNET DtMin= 0
UNET MaxCRTS= 0
UNET WFStab= 0
UNET SFStab= 0
UNET WFX= 1
UNET SFX= 1
UNET Gravity=32.17405
UNET 1D Methodology=Finite Difference
UNET DSS MLevel= 1
UNET Pardiso=0
UNET DZMax Abort= 0
UNET Use Existing IB Tables= 0
UNET Froude Reduction=False
UNET Froude Limit= 0
UNET Froude Power= 0
UNET D1 Cores= 0
UNET WindReference=Eulerian
UNET WindDragFormulation=Hsu (1988)
UNET D2 Coriolis=0
UNET D2 Cores= 0
UNET D2 Theta= 1
UNET D2 Theta Warmup= 1
UNET D2 Z Tol= 0.01
UNET D2 Volume Tol= 0.01
UNET D2 Max Iterations= 20
UNET D2 Equation= 0
UNET D2 RampUpFraction=0.1
UNET D2 TimeSlices= 1
UNET D2 Turbulence Formulation=Non-Conservative (original)
UNET D2 Eddy Viscosity=0.3
UNET D2 Transverse Eddy Viscosity=0.1
UNET D2 Smagorinsky Mixing=0
UNET D2 BCVolumeCheck=0
UNET D2 Cores=0
UNET D2 SolverType=PARDISO (Direct)
UNET D2 Minimum Iterations= 3
UNET D2 Maximum Iterations= 30
UNET D2 Restart Number= 10
UNET D2 Relaxation Coeff=1.3
UNET D2 SOR Precondition Iterations= 10
UNET D2 ILUT Maximum Fill= 8
UNET D2 ILUT Tolerance=1E-08
UNET D2 Convergence Tolerance=0.00001
UNET D1D2 MaxIter= 0
UNET D1D2 ZTol=0.01
UNET D1D2 QTol=0.1
UNET D1D2 MinQTol=1
Write IC File= 0
Write IC File at Fixed DateTime=0
Write IC File at Sim End=0
Echo Input=False
Echo Parameters=False
Echo Output=False
Write Detailed= 0
HDF Write Warmup=0
HDF Write Time Slices=0
HDF Flush=0
HDF Compression= 1
HDF Chunk Size= 1
HDF Spatial Parts= 1
HDF Use Max Rows=0
HDF Fixed Rows= 1
Calibration Method= 0
Calibration Iterations= 20
Calibration Max Change=0.05
Calibration Tolerance=0.2
Calibration Maximum=1.5
Calibration Minimum=0.5
Calibration Optimization Method= 1
WQ AD Non Conservative
WQ ULTIMATE=-1
WQ Max Comp Step=1HOUR
WQ Output Interval=15MIN
WQ Output Selected Increments= 0
WQ Create Restart=0
WQ Fixed Restart=0
WQ System Summary=0
WQ Write To DSS=0
Sorting and Armoring Iterations= 10
XS Update Threshold= 0.02
Bed Roughness Predictor= 0
Hydraulics Update Threshold= 0.02
Energy Slope Method= 1
Volume Change Method= 1
Sediment Retention Method= 0
Sediment TS Multiplier= 1
Warm Up Method= 0
XS Weighting Method= 0
Number of US Weighted Cross Sections= 1
Number of DS Weighted Cross Sections= 1
Upstream XS Weight=0
Main XS Weight=1
Downstream XS Weight=0
Number of DS XS's Weighted with US Boundary= 1
Upstream Boundary Weight= 1
Weight of XSs Associated with US Boundary= 0
Number of US XS's Weighted with DS Boundary= 1
Downstream Boundary Weight= 0.5
Weight of XSs Associated with DS Boundary= 0.5
Percentile Method= 0
Sediment Output Level= 3
Mass or Volume Output= 0
Output Increment Type= 1
Profile and TS Output Increment= 1
Transport Output Increment 1
XS Output Flag= 0
XS Output Increment= 10
Read HDF5 Sediment Hotstart= 0
Sediment Hotstart Type= 0
Write Gradation File= 0
Read Gradation Hotstart= 0
Write HDF5 File= 1
Write Binary Output= 1
Write DSS Sediment File= 0
DSS Sediment Output Type= 1
SV Curve= 0
Specific Gage Flag= 0
Subcell Erosion Methods= 0
Subcell Deposition Methods= 0
Advection Scheme= 1
Matrix Solver= 0
Implicit Weighting Factor= 1
Maximum Outer Loop Convergence Iterations= 5
Convergence Maximum Absolute= 0.001
Convergence RMSE= 0.0001
Grain Fractions Max Abs Error= 0.001
Max Subgrid Regions= 1
Max Subgrid Length Scale= 3.402823E+38
Initial Layer Thickness= 3.402823E+38
Min Layer Thickness= 3.402823E+38
Max Layer Thickness= 3.402823E+38
Number of Layers= 5

--- LILAURELFK.f01 (steady flow) ---

Flow Title=Flows
Program Version=6.31
Number of Profiles= 1
Profile Names=01pct
River Rch & RM=LILAURELFK,Main            ,17962
     337
River Rch & RM=LILAURELFK,Main            ,16198
     377
River Rch & RM=LILAURELFK,Main            ,15008
     420
River Rch & RM=LILAURELFK,Main            ,12339
     477
River Rch & RM=LILAURELFK,Main            ,8964
     530
River Rch & RM=LILAURELFK,Main            ,4353
     657
Boundary for River Rch & Prof#=LILAURELFK,Main            , 1
Up Type= 0
Dn Type= 3
Dn Slope=0.04016
DSS Import GetInterval= 0
DSS Import GetPeak= 0
DSS Import FillOption= 0

--- LILAURELFK.g01 (geometry) ---

Geom Title=Geometry
Program Version=6.31

River Reach=LILAURELFK      ,Main
Reach XY= 30
2215413.95487995718075.599637738     2214961.929      718693.937
     2214051.928      719075.622     2213699.546      720274.077
     2212379.987      721482.661     2212107.931       721973.89
     2212260.628      721995.496     2212153.402      722336.231
     2212394.982      722662.5722212379.72110237723153.731954325
     2212704.354      723382.217     2212629.092      723559.152
     2212862.545      723591.288     2212800.962      723803.193
     2213039.566      723988.255     2212885.409      724076.279
     2213104.868      724440.022     2212948.966      724649.694
     2213118.061      724826.744     2213108.131      725298.285
     2213661.886      726151.654     2214056.878      726330.535
     2214078.598      727146.846      2214369.97      727486.322
     2214220.049      727698.942     2214468.239      727880.685
     2214397.528      728338.347     2214643.886      729110.045
     2214392.892      730071.069     2214167.166      730332.651

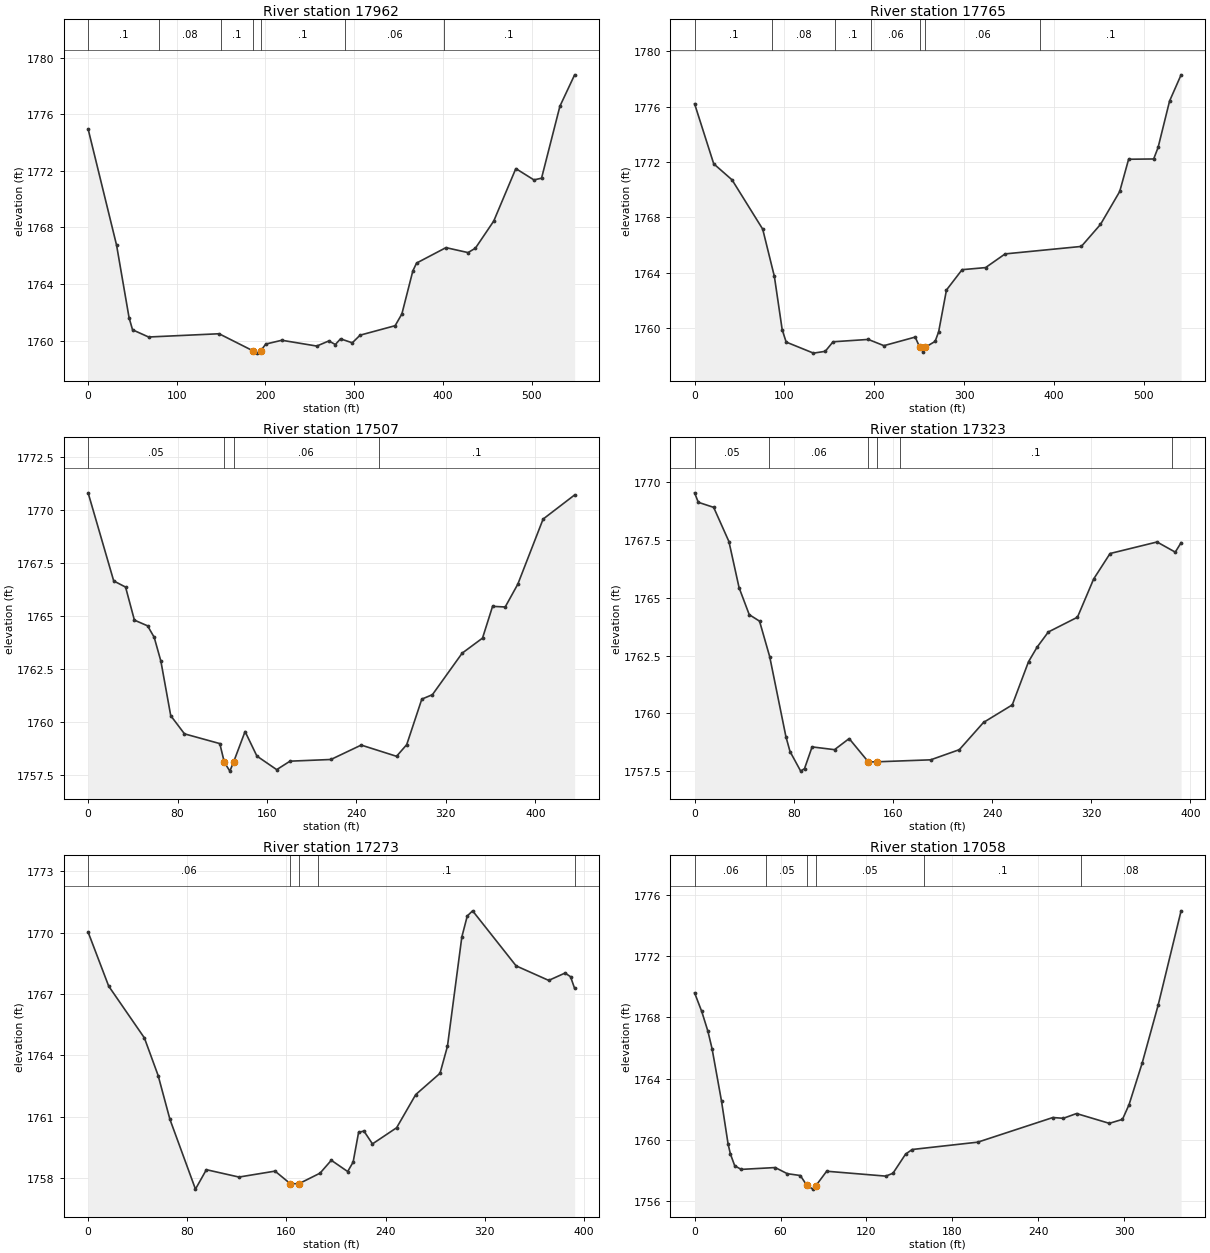
Type RM Length L Ch R = 1 ,17962   ,196.5,197.2,196.5
XS GIS Cut Line= 3
2215327.35061462717907.3399126782215467.46368263718207.026197014
 2215524.5467844718417.195799016
#Sta/Elev= 30
       0 1774.96    32.1 1766.74    46.2 1761.61    50.1 1760.76    68.2 1760.25
   147.7 1760.48  186.31 1759.26   190.8 1759.11   194.6 1759.27   200.3 1759.75
   218.4 1760.02   257.8 1759.61   271.4 1759.97   278.8 1759.72   284.6 1760.12
   297.9 1759.84   306.7 1760.38   346.2 1761.05   353.8 1761.88   366.2 1764.93
   370.4 1765.48   403.5 1766.57   428.4 1766.22   436.7 1766.53   457.4 1768.45
   482.3 1772.16   502.7 1771.36   511.3 1771.48     532 1776.57   548.6 1778.79
#Mann= 7 ,-1,0
       0      .1       0      80     .08       0     150      .1       0
  186.31    .045       0   194.6      .1       0     290     .06       0
  400.82      .1       0
Bank Sta=186.31,194.6
XS Rating Curve= 0 ,0
Exp/Cntr(USF)=0,0
Exp/Cntr=0.3,0.1

Type RM Length L Ch R = 1 ,17765   ,258,258.2,258
XS GIS Cut Line= 4
2215121.27534873718101.9314958612215197.99653567 718141.79250054
2215453.19290718 718251.135866572215515.46538185718417.195799016
#Sta/Elev= 30
       0  1776.2    21.3 1771.86    41.7  1770.7    75.8 1767.14    88.8 1763.72
    97.5 1759.87   101.9 1758.98   132.3 1758.18   145.4 1758.31   154.1    1759
   193.3 1759.17   210.7 1758.72   245.5 1759.34   250.41758.625   254.2 1758.29
   256.61758.598   267.7 1759.03   271.6 1759.72   280.3 1762.74   297.7 1764.21
   323.8 1764.36   345.6 1765.35   430.4 1765.89   451.7 1767.48   473.1 1769.86
     483 1772.19   510.9 1772.21   515.8 1773.04   528.6  1776.4   541.4 1778.29
#Mann= 7 ,-1,0
       0      .1       0   86.46     .08       0  156.46      .1       0
  196.46     .06       0   250.4    .045       0   256.6     .06       0
  384.09      .1       0
Bank Sta=250.4,256.6
XS Rating Curve= 0 ,0
Exp/Cntr(USF)=0,0
Exp/Cntr=0.3,0.1

Type RM Length L Ch R = 1 ,17507   ,184,184,184
XS GIS Cut Line= 2
2215067.88197018718209.6208834592215453.19290718718412.006426127
#Sta/Elev= 30
       0 1770.82    22.9 1766.66    33.5 1766.37    41.4 1764.81    53.2 1764.54
    59.1    1764    65.1 1762.87    73.9  1760.3    86.2 1759.44   117.8 1758.98
  121.811758.102   126.8 1757.68   130.2 1758.12   140.4 1759.55     151 1758.39
   168.7 1757.75   180.6 1758.15   217.2 1758.23   244.3 1758.91   275.9 1758.38
     285 1758.93   298.5 1761.08     308 1761.29   334.6 1763.25   352.8 1763.96
   361.8 1765.46   373.1 1765.43   384.4 1766.51     407 1769.58   435.2 1770.72
#Mann= 4 ,-1,0
       0     .05       0  121.81    .045       0   130.2     .06       0
     260      .1       0
Bank Sta=121.81,130.2
XS Rating Curve= 0 ,0
Exp/Cntr(USF)=0,0
Exp/Cntr=0.3,0.1

Type RM Length L Ch R = 1 ,17323   ,48.2,49.3,48.2
XS GIS Cut Line= 3
2215041.24232445 718340.856231792215124.46948684 718360.71725918
2215404.41539671718486.503765978
#Sta/Elev= 30
       0 1769.55       3 1769.14    15.4 1768.92    27.7 1767.44    35.9 1765.44
    44.1 1764.27    52.4 1763.99    60.6 1762.45    73.7 1758.98      77 1758.34
    85.6 1757.49    88.7  1757.6    94.8 1758.54   112.9 1758.42   124.7  1758.9
   140.2 1757.89  147.281757.894   190.5 1757.98   213.6 1758.42   233.1  1759.6
   256.3 1760.36   269.4 1762.23   276.3 1762.86   285.4 1763.52   308.9 1764.16
     322 1765.82   335.2 1766.92   373.1 1767.42   387.8 1766.98   392.5 1767.39
#Mann= 6 ,-1,0
       0     .05       0      60     .06       0   140.2    .045       0
  147.28     .06       0  165.56      .1       0  385.56     .06       0
Bank Sta=140.2,147.28
XS Rating Curve= 0 ,0
Exp/Cntr(USF)=0,0
Exp/Cntr=0.3,0.1

Type RM Length L Ch R = 1 ,17273   ,215.5,214.9,215.5
XS GIS Cut Line= 3
2215028.00163952718372.0664176882215111.22880192718391.927445077
2215391.17471178718517.713951875
#Sta/Elev= 30
       0 1770.02    16.6 1767.38    45.4 1764.85    56.5 1763.01      66 1760.87
    86.6 1757.46    95.4 1758.41   121.7 1758.05   150.8 1758.34  163.071757.728
   169.9 1757.72   187.1 1758.24   196.2 1758.87   209.4 1758.32   213.8 1758.78
   218.2 1760.23   222.5  1760.3   229.4 1759.67   248.9 1760.46   264.3 1762.08
   283.9 1763.12   289.9 1764.44   301.5 1769.78   305.9 1770.81   310.2 1771.06
   345.3 1768.37   371.6 1767.66   384.8 1768.02   389.2 1767.84   392.5 1767.27
#Mann= 5 ,-1,0
       0     .06       0  163.07    .045       0   169.9     .06       0
  185.56      .1       0  392.47     .06       0
Bank Sta=163.07,169.9
XS Rating Curve= 0 ,0
Exp/Cntr(USF)=0,0
Exp/Cntr=0.3,0.1

Type RM Length L Ch R = 1 ,17058   ,328.6,328.6,328.6
XS GIS Cut Line= 2
2215011.92366497718428.8122102282215178.37798976718724.836094648
#Sta/Elev= 30
       0  1769.6       5 1768.38     9.3 1767.09    12.2 1765.95    18.8 1762.52
    23.4 1759.71      25 1759.07      28  1758.3    32.5 1758.06    56.3 1758.18
    64.7 1757.78    73.8 1757.66    78.4 1757.01    82.7 1756.77   84.771757.007
    92.2 1757.94   133.5 1757.62   138.5 1757.81   147.3 1759.06   151.9 1759.36
   197.7 1759.84   250.1 1761.45   257.4  1761.4   266.6 1761.71   289.5 1761.07
   298.7 1761.33   303.3  1762.3   312.5 1765.03   323.6  1768.8   339.6 1774.96
#Mann= 6 ,-1,0
       0     .06       0      50     .05       0    78.4    .045       0
   84.77     .05       0     160      .1       0     270     .08       0
Bank Sta=78.4,84.77
XS Rating Curve= 0 ,0
Exp/Cntr(USF)=0,0
Exp/Cntr=0.3,0.1

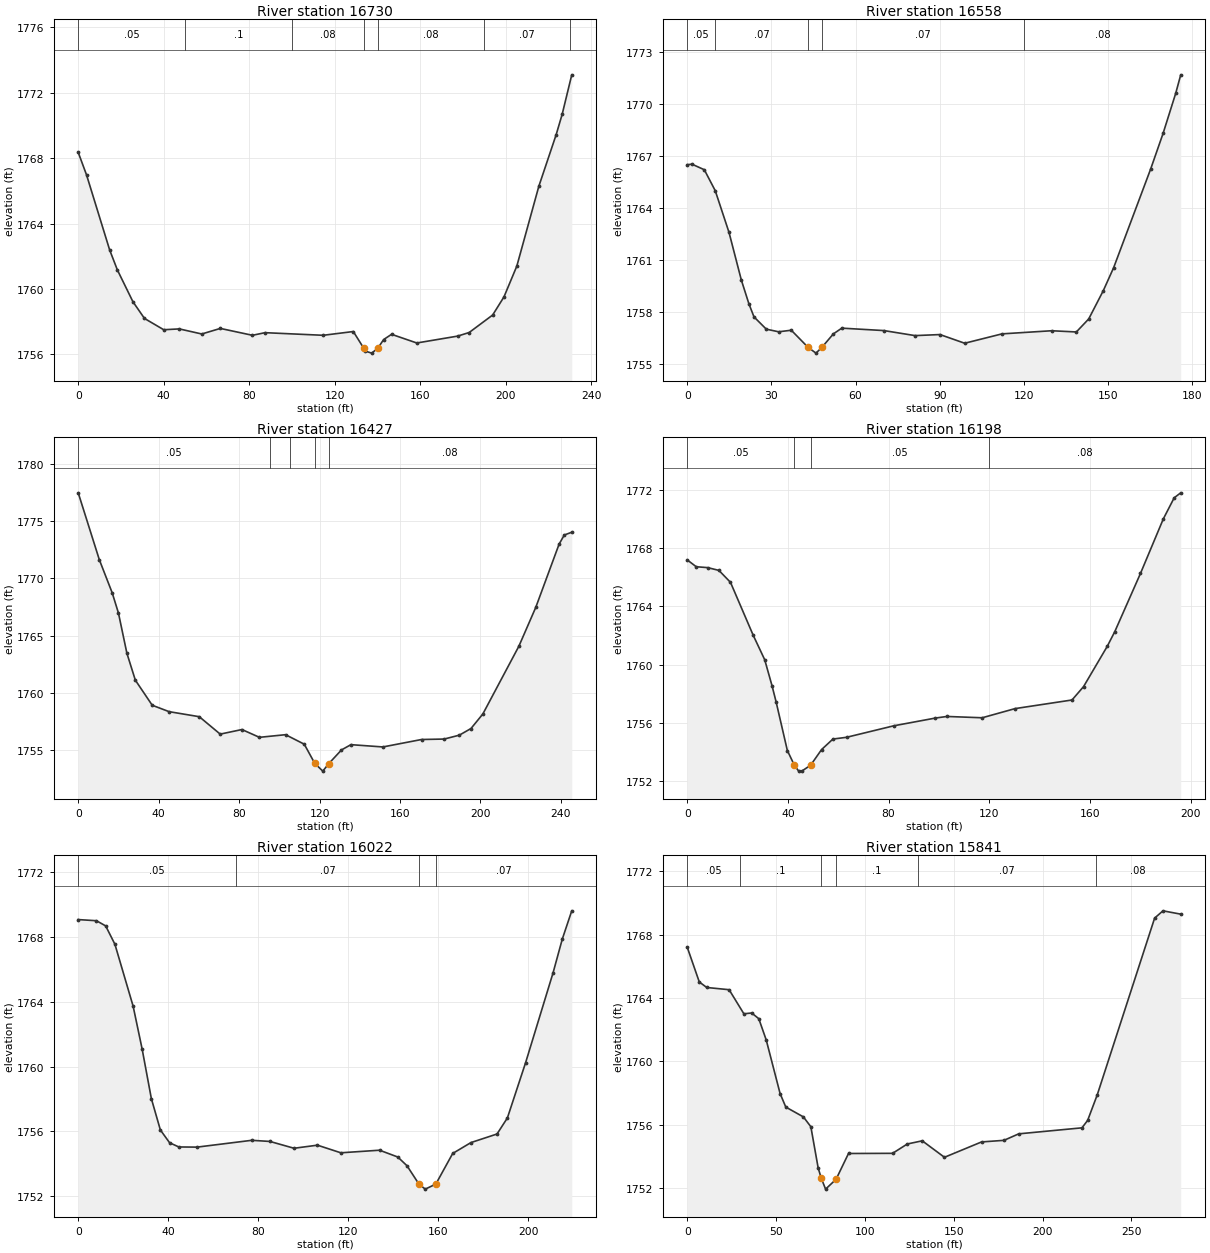
Type RM Length L Ch R = 1 ,16730   ,171.6,171.6,171.6
XS GIS Cut Line= 2
2214869.11342041718594.320771805 2215025.1643499718764.558149426
#Sta/Elev= 30
       0 1768.35     3.9 1766.97    14.7 1762.39    18.3 1761.17    25.6 1759.22
      31  1758.2      40 1757.51    47.3 1757.56    57.8 1757.25    66.5 1757.59
    81.5 1757.17    87.4 1757.33   114.6 1757.17   128.7  1757.4  133.621756.373
   134.4  1756.2   137.3 1756.08   140.1 1756.37   142.9 1756.91   146.6 1757.23
   158.4  1756.7   177.5 1757.12   182.9 1757.34   193.9 1758.41   199.2 1759.52
   205.2  1761.4   215.5 1766.28   223.6 1769.43   226.4 1770.67   230.9 1773.09
#Mann= 7 ,-1,0
       0     .05       0      50      .1       0     100     .08       0
  133.62    .045       0   140.1     .08       0     190     .07       0
     230     .08       0
Bank Sta=133.62,140.1
XS Rating Curve= 0 ,0
Exp/Cntr(USF)=0,0
Exp/Cntr=0.3,0.1

Type RM Length L Ch R = 1 ,16558   ,130.8,131.2,130.8
XS GIS Cut Line= 2
2214792.34780567718655.6832899362214867.25225183718814.855238012
#Sta/Elev= 30
       0  1766.5     1.7 1766.53     6.1 1766.21      10    1765    14.9  1762.6
    19.3 1759.85      22 1758.48    23.8 1757.73    28.2 1757.02    32.6 1756.87
    37.1 1756.96    43.1 1755.97    45.9 1755.64   47.99 1755.97    52.1 1756.75
    55.1 1757.08    70.1 1756.94    81.2 1756.65    90.1 1756.71    98.9 1756.21
   112.2 1756.75   129.9 1756.93   138.7 1756.86   143.1 1757.61   148.3 1759.24
     152 1760.57   165.2 1766.26   169.6  1768.3   174.1 1770.61   175.9 1771.68
#Mann= 5 ,-1,0
       0     .05       0      10     .07       0    43.1    .045       0
   47.99     .07       0     120     .08       0
Bank Sta=43.1,47.99
XS Rating Curve= 0 ,0
Exp/Cntr(USF)=0,0
Exp/Cntr=0.3,0.1

Type RM Length L Ch R = 1 ,16427   ,229.8,229.3,229.8
XS GIS Cut Line= 3
2214646.05461432718690.086710502 2214662.8891969718742.643096547
2214826.87526548718839.068696062
#Sta/Elev= 30
       0 1777.46    10.5 1771.62    16.9 1768.73      20 1766.97    24.2 1763.46
    28.4 1761.11    36.8 1758.92    45.2 1758.36    60.2 1757.92    70.6  1756.4
    81.4  1756.8    90.1 1756.12   103.1 1756.35   112.4 1755.52   117.61753.853
   121.6 1753.17   124.61753.827   130.9 1755.02   135.6 1755.48   151.5 1755.28
   170.7 1755.93     182 1755.97   189.5 1756.31   195.3 1756.89   201.2 1758.16
   219.1 1764.07   227.5 1767.46   239.1 1772.98   241.7 1773.78   245.4 1774.02
#Mann= 5 ,-1,0
       0     .05       0   95.19     .07       0  105.19     .08       0
   117.6    .045       0   124.6     .08       0
Bank Sta=117.6,124.6
XS Rating Curve= 0 ,0
Exp/Cntr(USF)=0,0
Exp/Cntr=0.3,0.1

Type RM Length L Ch R = 1 ,16198   ,176,176,176
XS GIS Cut Line= 2
2214533.73986485718758.0105091832214625.48163884718931.296157288
#Sta/Elev= 30
       0 1767.19     3.6 1766.72     8.1 1766.66    12.6 1766.47    17.2 1765.65
    26.2 1762.03    30.8 1760.34    33.7 1758.56    35.3 1757.47    39.8 1754.11
    42.6  1753.1    44.3  1752.7    45.6 1752.71   49.041753.105    53.4 1754.18
    57.9  1754.9    63.3 1755.02    82.1 1755.81    98.6 1756.34   103.2 1756.45
   117.2 1756.36   130.3 1756.99   152.9 1757.58   157.5  1758.5   166.9 1761.26
   169.9 1762.27   180.1 1766.26   189.2 1770.01   193.5 1771.45   196.1 1771.79
#Mann= 4 ,-1,0
       0     .05       0    42.6    .045       0   49.04     .05       0
     120     .08       0
Bank Sta=42.6,49.04
XS Rating Curve= 0 ,0
Exp/Cntr(USF)=0,0
Exp/Cntr=0.3,0.1

Type RM Length L Ch R = 1 ,16022   ,140.8,180.4,140.8
XS GIS Cut Line= 2
2214453.64573224 718793.143843822214490.24676843  719009.3453134
#Sta/Elev= 30
       0 1769.06     8.1 1768.99    12.2 1768.67    16.3 1767.54    24.4 1763.72
    28.4 1761.08    32.5 1758.02    36.5 1756.09    40.6  1755.3    44.7 1755.04
    52.8 1755.03    77.1 1755.45    85.2 1755.38    95.9 1754.96   106.3 1755.15
   116.7 1754.68   133.9 1754.84     142 1754.42   146.1 1753.88   151.4 1752.75
   154.2 1752.44   158.9 1752.75   166.4 1754.64   174.5 1755.31   186.1 1755.84
   190.7 1756.83   198.8 1760.24     211 1765.78   215.1 1767.86   219.3  1769.6
#Mann= 4 ,-1,0
       0     .05       0      70     .07       0   151.4    .045       0
   158.9     .07       0
Bank Sta=151.4,158.9
XS Rating Curve= 0 ,0
Exp/Cntr(USF)=0,0
Exp/Cntr=0.3,0.1

Type RM Length L Ch R = 1 ,15841   ,132.6,261.2,132.6
XS GIS Cut Line= 3
2214293.44031793718838.6399529462214360.67942074719059.395782246
2214388.65710347719097.231209379
#Sta/Elev= 30
       0 1767.22     6.8 1765.02      11 1764.67    23.6 1764.53    31.9 1763.01
    36.3 1763.06    40.3  1762.7    44.5 1761.35    52.3 1757.97    55.5 1757.12
    65.4  1756.5    69.6 1755.88    73.7 1753.29    75.41752.643    77.9 1751.94
    83.81752.562    90.8 1754.19   115.6  1754.2   123.9 1754.79   132.3 1754.99
   144.8 1753.95   165.7 1754.92   178.3 1755.02   186.6 1755.43   222.2 1755.81
   225.4 1756.28   230.8 1757.89   263.1 1769.05   267.8 1769.51   277.8  1769.3
#Mann= 6 ,-1,0
       0     .05       0      30      .1       0    75.4    .045       0
    83.8      .1       0     130     .07       0     230     .08       0
Bank Sta=75.4,83.8
XS Rating Curve= 0 ,0
Exp/Cntr(USF)=0,0
Exp/Cntr=0.3,0.1

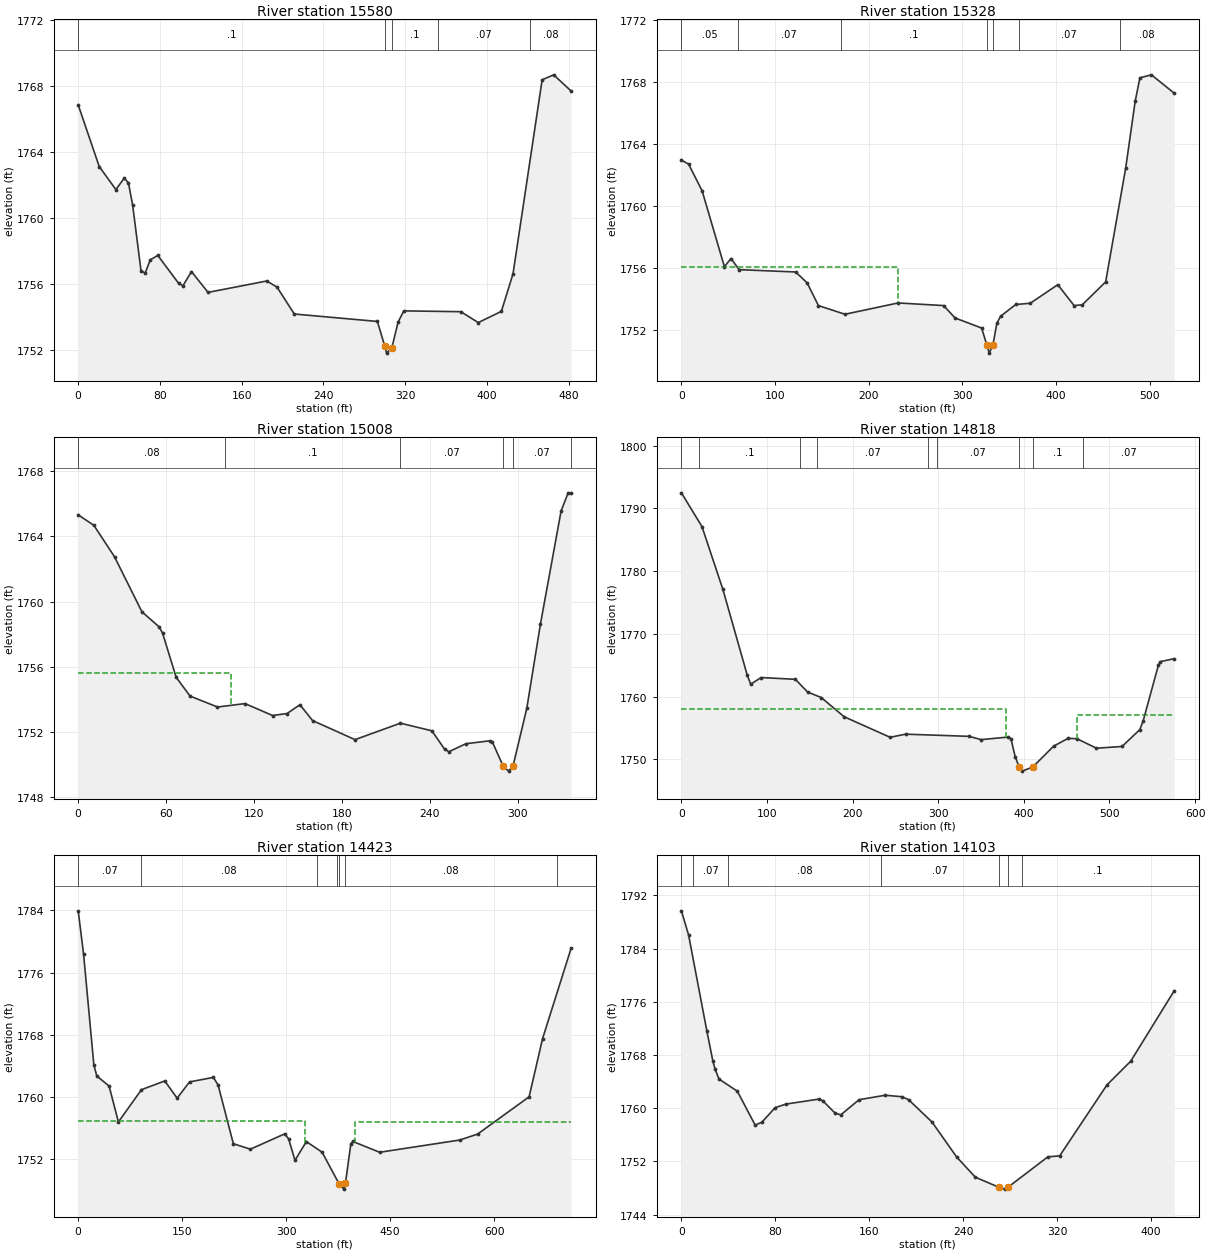
Type RM Length L Ch R = 1 ,15580   ,299.1,251.8,299.1
XS GIS Cut Line= 3
2214055.75264173718793.219868133  2214098.314682718980.373324746
2214304.21188767719185.247188768
#Sta/Elev= 30
       0 1766.87    20.6 1763.13    36.9 1761.74    45.1 1762.43    49.2 1762.14
    53.3  1760.8    61.5 1756.82    65.6 1756.68    70.5 1757.48    77.9 1757.75
    98.4 1756.05   102.5 1755.91   110.9 1756.77   127.1 1755.51   184.6  1756.2
   194.6 1755.83   211.5  1754.2   292.8 1753.75     3001752.267   301.8 1751.83
     307 1752.15   313.1 1753.71   318.7 1754.39   374.5 1754.34   391.6 1753.68
   414.2 1754.36   425.6 1756.64   454.1 1768.39   465.4 1768.69   482.4 1767.71
#Mann= 5 ,-1,0
       0      .1       0     300    .045       0     307      .1       0
  351.93     .07       0  441.93     .08       0
Bank Sta=300,307
XS Rating Curve= 0 ,0
Exp/Cntr(USF)=0,0
Exp/Cntr=0.3,0.1

Type RM Length L Ch R = 1 ,15328   ,318.5,320.2,318.5
XS GIS Cut Line= 4
2213773.69449092719062.4539186562213874.42906797719128.122353429
2214148.71183071719172.5360708442214266.62446591719222.919396141
#Sta/Elev= 30
       0 1762.97     7.7  1762.7    22.1 1760.98    45.9 1756.08    52.9 1756.61
    61.6 1755.89     122 1755.74   134.2 1755.04   146.3 1753.57   174.7 1753.01
   231.4 1753.74     280 1753.57   292.2 1752.77   320.6 1752.12   326.11751.027
   328.7  1750.5   332.7 1751.05   336.8 1752.42   340.8 1752.88     357 1753.64
   372.5 1753.72   401.9 1754.92   419.3 1753.57     428 1753.62     453  1755.1
   474.4 1762.45   484.5 1766.75   489.6 1768.28   501.9 1768.47   526.3 1767.28
#Mann= 7 ,-1,0
       0     .05       0      60     .07       0  170.25      .1       0
   326.1    .045       0   332.7      .1       0  360.25     .07       0
   468.1     .08       0
#XS Ineff= 2 , 0
          231.63 1756.09
Permanent Ineff=
       F       F
Bank Sta=326.1,332.7
XS Rating Curve= 0 ,0
Exp/Cntr(USF)=0,0
Exp/Cntr=0.3,0.1

Type RM Length L Ch R = 1 ,15008   ,189.9,189.9,189.9
XS GIS Cut Line= 2
 2213731.0727375719270.2158236882214017.92973887719446.077904925
#Sta/Elev= 30
       0 1765.32    10.7 1764.68    24.8 1762.75    43.5 1759.38    55.3 1758.45
    57.6 1758.07    66.9 1755.36    76.4 1754.21    95.1 1753.54   113.9 1753.75
   132.7 1753.02   142.6 1753.14   151.4 1753.68     160 1752.71     189 1751.54
     220 1752.55   241.5 1752.08   250.2 1750.95   253.1  1750.8   264.7 1751.29
   281.2 1751.47   282.8 1751.39  290.081749.926   293.8 1749.61   296.9 1749.93
   306.3 1753.47   315.6 1758.63   329.7 1765.56   334.4 1766.64   336.5 1766.67
#Mann= 6 ,-1,0
       0     .08       0     100      .1       0     220     .07       0
  290.08    .045       0   296.9     .07       0  336.47     .08       0
#XS Ineff= 2 , 0
          104.67  1755.6
Permanent Ineff=
       F       F
Bank Sta=290.08,296.9
XS Rating Curve= 0 ,0
Exp/Cntr(USF)=0,0
Exp/Cntr=0.3,0.1

Type RM Length L Ch R = 1 ,14818   ,395.6,395.6,395.6
XS GIS Cut Line= 4
2213600.60635418719808.7527084512213697.49679449719790.956505128
2213944.86382294 719458.28772623 2214000.6495815 719486.82927712
#Sta/Elev= 30
       0 1792.48      24  1787.1    48.4 1777.11    76.8 1763.47    80.9 1761.99
    93.1 1763.05   133.1 1762.77   147.4 1760.74   163.3 1759.87   190.1  1756.8
   243.8 1753.53   261.8 1754.03   336.1 1753.68     350 1753.16   381.9 1753.57
   384.9 1753.31   389.8 1750.47  394.411748.817     398 1748.14   410.5 1748.81
   434.7 1752.11   451.6 1753.36   461.9 1753.31   484.8 1751.79   514.7 1752.07
   535.5 1754.77   539.3 1756.13   557.2 1765.05   559.3 1765.58   575.7 1766.06
#Mann= 9 ,-1,0
       0     .05       0      20      .1       0  138.51     .08       0
  158.51     .07       0  288.51     .06       0  298.51     .07       0
  394.41    .045       0   410.5      .1       0  468.51     .07       0
#XS Ineff= 2 , 0
          378.72 1758.11   462.4         1757.04
Permanent Ineff=
       F       F
Bank Sta=394.41,410.5
XS Rating Curve= 0 ,0
Exp/Cntr(USF)=0,0
Exp/Cntr=0.3,0.1

Type RM Length L Ch R = 1 ,14423   ,319.9,319.9,319.9
XS GIS Cut Line= 4
2213544.15481988719958.9253769842213744.83271797720057.890063663
2214010.36255154719723.9239415432214059.66159398719758.952208543
#Sta/Elev= 30
       0 1783.95     7.7 1778.43    22.6  1764.1    26.8 1762.67    44.6 1761.36
      58 1756.74    91.3  1760.9   124.9 1762.02   142.7  1759.8   160.6  1761.9
     195 1762.48   201.8  1761.5   223.8 1753.93   248.4 1753.23   297.8  1755.2
   303.5 1754.56   312.7 1751.79   329.1 1754.21   351.9 1752.83  376.031748.805
   383.1 1748.08  385.49 1748.86   393.3 1753.94   396.2 1754.22   434.8 1752.83
   550.5 1754.41   576.2 1755.18   650.4 1759.98   669.8 1767.48   710.9  1779.1
#Mann= 7 ,-1,0
       0     .07       0      90     .08       0  343.75     .07       0
  373.75     .08       0  376.03    .045       0  385.49     .08       0
  690.41     .07       0
#XS Ineff= 2 , 0
          327.25 1756.83  399.93         1756.71
Permanent Ineff=
       F       F
Bank Sta=376.03,385.49
XS Rating Curve= 0 ,0
Exp/Cntr(USF)=0,0
Exp/Cntr=0.3,0.1

Type RM Length L Ch R = 1 ,14103   ,353.6,376.4,353.6
XS GIS Cut Line= 3
2213495.47781213720033.4844703722213743.01089893720237.816027874
2213841.09004653720249.492116875
#Sta/Elev= 30
       0 1789.67     6.1 1786.05    21.7 1771.57    26.8 1767.07    28.7 1765.86
      32 1764.37    47.6 1762.55    62.8 1757.44    68.5 1757.88    79.8 1760.07
    89.1 1760.61   116.8 1761.35   120.2 1761.14     131 1759.22   135.8    1759
   151.3 1761.27   173.6 1761.94     188 1761.71   193.5 1761.26   213.4 1757.91
   234.3 1752.67   250.3 1749.61   270.6 1748.08   275.8 1747.82  277.871748.079
   312.1 1752.68   322.1 1752.82   362.4  1763.5   382.6 1767.06   419.7 1777.67
#Mann= 7 ,-1,0
       0      .1       0      10     .07       0      40     .08       0
     170     .07       0   270.6    .045       0  277.87     .07       0
     290      .1       0
Bank Sta=270.6,277.87
XS Rating Curve= 0 ,0
Exp/Cntr(USF)=0,0
Exp/Cntr=0.3,0.1

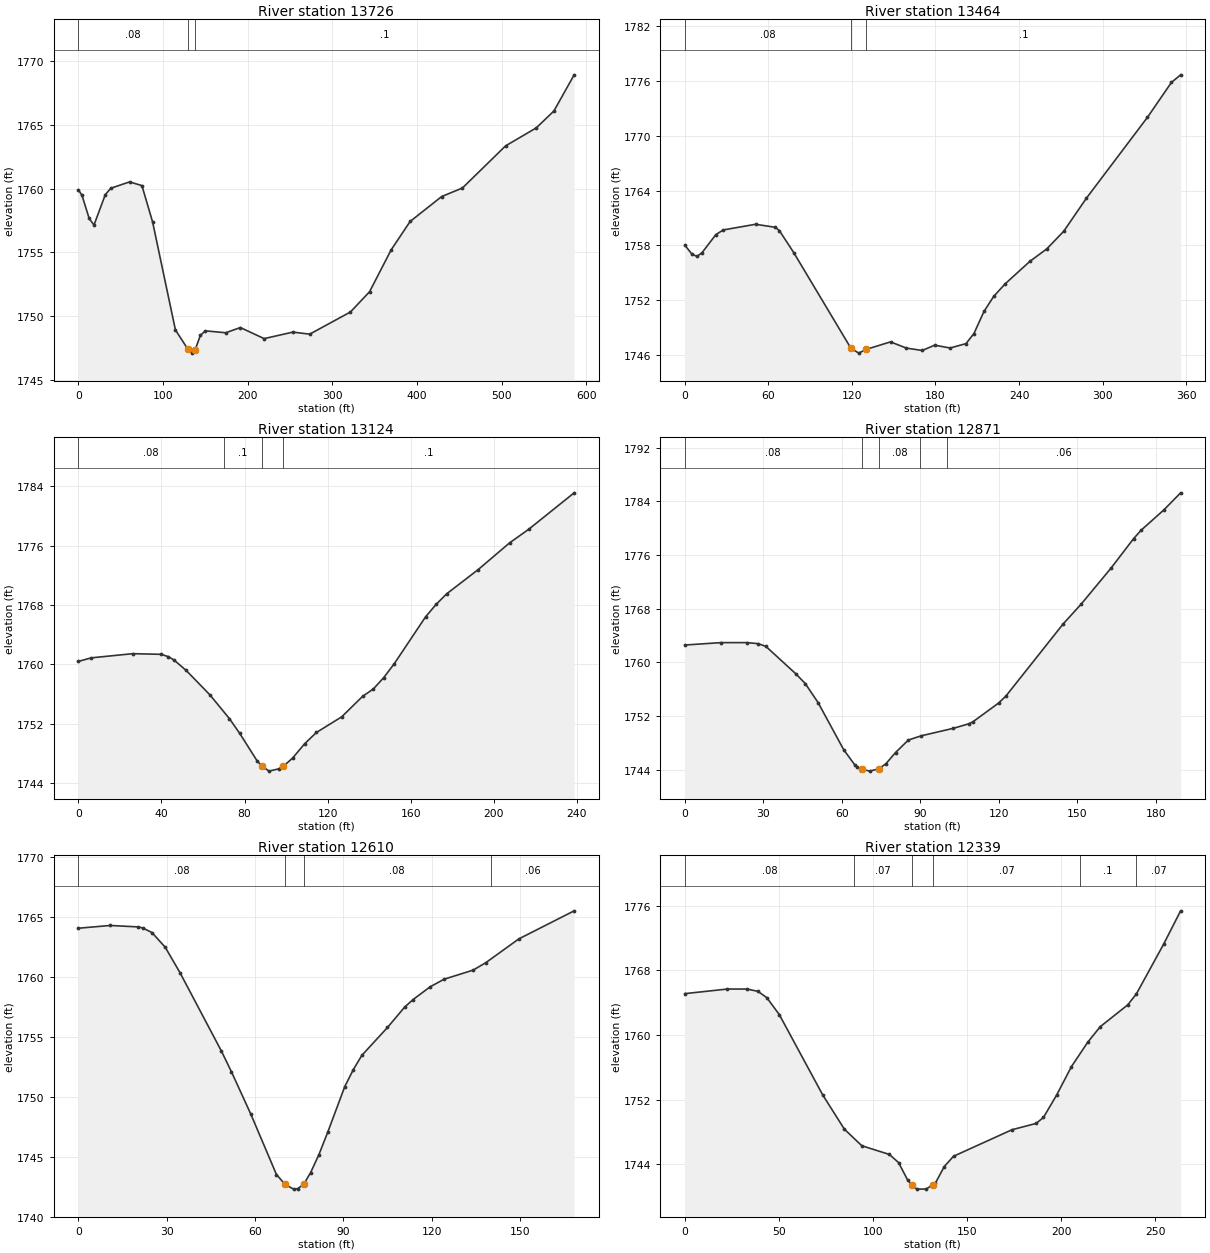
Type RM Length L Ch R = 1 ,13726   ,274.5,262.1,274.5
XS GIS Cut Line= 3
2213391.60799479720351.6307847332213701.97190037720636.886060476
2213835.64224386720732.247385093
#Sta/Elev= 30
       0 1759.91     4.3 1759.48    12.8 1757.66    18.5 1757.14    31.8 1759.52
    38.3 1760.03    60.5 1760.53    75.1 1760.24    87.7 1757.39   114.7  1748.9
   129.3  1747.4   134.6 1747.08     1381747.345   144.2 1748.48   150.1 1748.83
   174.2 1748.68   191.4 1749.09   219.5 1748.22   253.5 1748.73   273.3 1748.57
   321.4 1750.31     344  1751.9   369.5 1755.19   391.9 1757.42   429.2 1759.38
   453.7 1760.05   504.7 1763.36   540.9 1764.77   561.8  1766.1   585.7 1768.94
#Mann= 3 ,-1,0
       0     .08       0   129.3    .045       0     138      .1       0
Bank Sta=129.3,138
XS Rating Curve= 0 ,0
Exp/Cntr(USF)=0,0
Exp/Cntr=0.3,0.1

Type RM Length L Ch R = 1 ,13464   ,350.7,340.4,350.7
XS GIS Cut Line= 3
2213246.76250633  720531.36488762213392.28151403720719.212361568
2213413.33496943720835.679964421
#Sta/Elev= 30
       0 1758.03     5.2 1757.03     8.8  1756.8    12.4 1757.21    22.3 1759.18
    27.6 1759.69    50.8 1760.31      65 1759.98    67.9 1759.62    78.2 1757.22
   119.2 1746.78   124.9 1746.23   130.11746.633   147.7 1747.46   159.1 1746.78
   170.5 1746.52   179.4  1747.1   190.5 1746.79   201.9 1747.27   207.6 1748.37
   214.8 1750.78   221.8 1752.43     230  1753.8   247.7 1756.25   259.9 1757.62
   272.1 1759.55   288.4 1763.17   332.2    1772   349.4 1775.81     356 1776.64
#Mann= 3 ,-1,0
       0     .08       0   119.2    .045       0   130.1      .1       0
Bank Sta=119.2,130.1
XS Rating Curve= 0 ,0
Exp/Cntr(USF)=0,0
Exp/Cntr=0.3,0.1

Type RM Length L Ch R = 1 ,13124   ,252.5,252.5,252.5
XS GIS Cut Line= 2
2213043.80817588720772.759017223 2213189.5590811720961.754696512
#Sta/Elev= 30
       0  1760.4     6.3 1760.88    26.2 1761.44    39.9 1761.35    43.3 1761.04
      46  1760.6    51.9 1759.19    63.3 1755.91    72.7 1752.71    77.6 1750.75
    86.1    1747   88.48  1746.3    91.8 1745.63    96.5 1745.94    98.71746.281
   103.2  1747.4   108.9  1749.3   114.6 1750.83   126.8 1752.94   136.9 1755.71
     142 1756.68     147 1758.21   152.1 1760.09   167.2 1766.41   172.3 1768.09
   177.3 1769.49   192.5 1772.76   207.6 1776.35   216.8 1778.18   238.7 1783.09
#Mann= 4 ,-1,0
       0     .08       0      70      .1       0   88.48    .045       0
    98.7      .1       0
Bank Sta=88.48,98.7
XS Rating Curve= 0 ,0
Exp/Cntr(USF)=0,0
Exp/Cntr=0.3,0.1

Type RM Length L Ch R = 1 ,12871   ,261,261,261
XS GIS Cut Line= 2
2212882.26820567720943.850348908 2212992.7826283721097.609545618
#Sta/Elev= 30
       0 1762.58    13.8 1762.94    23.8 1762.94    28.1 1762.78      31 1762.37
    42.4  1758.3      46 1756.85    50.9 1754.02    60.7 1746.99    64.9 1744.75
    65.7 1744.44    67.5 1744.14    70.6  1743.8      74 1744.13    76.8 1744.89
    80.5 1746.57    85.4 1748.43    90.3 1749.06   102.6 1750.18   108.4 1750.84
     110 1751.13   119.9 1753.95   122.7    1755   144.5 1765.71   151.4 1768.67
   162.8 1774.03   171.4 1778.41   174.3 1779.68   182.9 1782.67   189.4 1785.25
#Mann= 5 ,-1,0
       0     .08       0    67.5    .045       0      74     .08       0
      90     .07       0     100     .06       0
Bank Sta=67.5,74
XS Rating Curve= 0 ,0
Exp/Cntr(USF)=0,0
Exp/Cntr=0.3,0.1

Type RM Length L Ch R = 1 ,12610   ,271,271,271
XS GIS Cut Line= 2
2212704.48413447721104.0161788142212794.17699922721246.563767431
#Sta/Elev= 30
       0 1764.04    10.8 1764.27    20.3 1764.15      22 1764.05      25 1763.68
    29.5 1762.46    34.5 1760.35    48.6  1753.8      52 1752.08    58.6 1748.54
    67.3 1743.51    70.2  1742.7    73.1  1742.3    74.5 1742.34   76.531742.698
    78.9 1743.68    81.7 1745.17    84.7 1747.04    90.5 1750.85    93.4 1752.26
    96.3 1753.45     105 1755.77   110.8 1757.46   113.7  1758.1   119.5 1759.16
   124.2 1759.79   134.1 1760.55   138.4 1761.17   149.6 1763.15   168.4 1765.49
#Mann= 4 ,-1,0
       0     .08       0    70.2    .045       0   76.53     .08       0
     140     .06       0
Bank Sta=70.2,76.53
XS Rating Curve= 0 ,0
Exp/Cntr(USF)=0,0
Exp/Cntr=0.3,0.1

Type RM Length L Ch R = 1 ,12339   ,344.9,344.9,344.9
XS GIS Cut Line= 2
2212499.27180392721247.9824999642212649.82768403721464.206370337
#Sta/Elev= 30
       0 1765.12    22.6 1765.69    33.1 1765.69    38.9  1765.4    43.6 1764.62
    50.2 1762.53    73.3 1752.57    84.8 1748.33    94.1 1746.27   108.7  1745.2
   113.6 1744.19   118.4 1742.04   120.6 1741.45   123.3  1740.9   128.2 1740.91
  131.881741.443   133.1 1741.62   137.9  1743.7   142.8 1744.97   173.9 1748.26
   186.7 1749.04   190.6 1749.78   197.6 1752.55   205.5 1756.09   214.1 1759.09
   220.8 1761.03   235.4 1763.73     240 1765.09   254.4 1771.22   263.5 1775.38
#Mann= 6 ,-1,0
       0     .08       0      90     .07       0   120.6    .045       0
  131.88     .07       0     210      .1       0     240     .07       0
Bank Sta=120.6,131.88
XS Rating Curve= 0 ,0
Exp/Cntr(USF)=0,0
Exp/Cntr=0.3,0.1

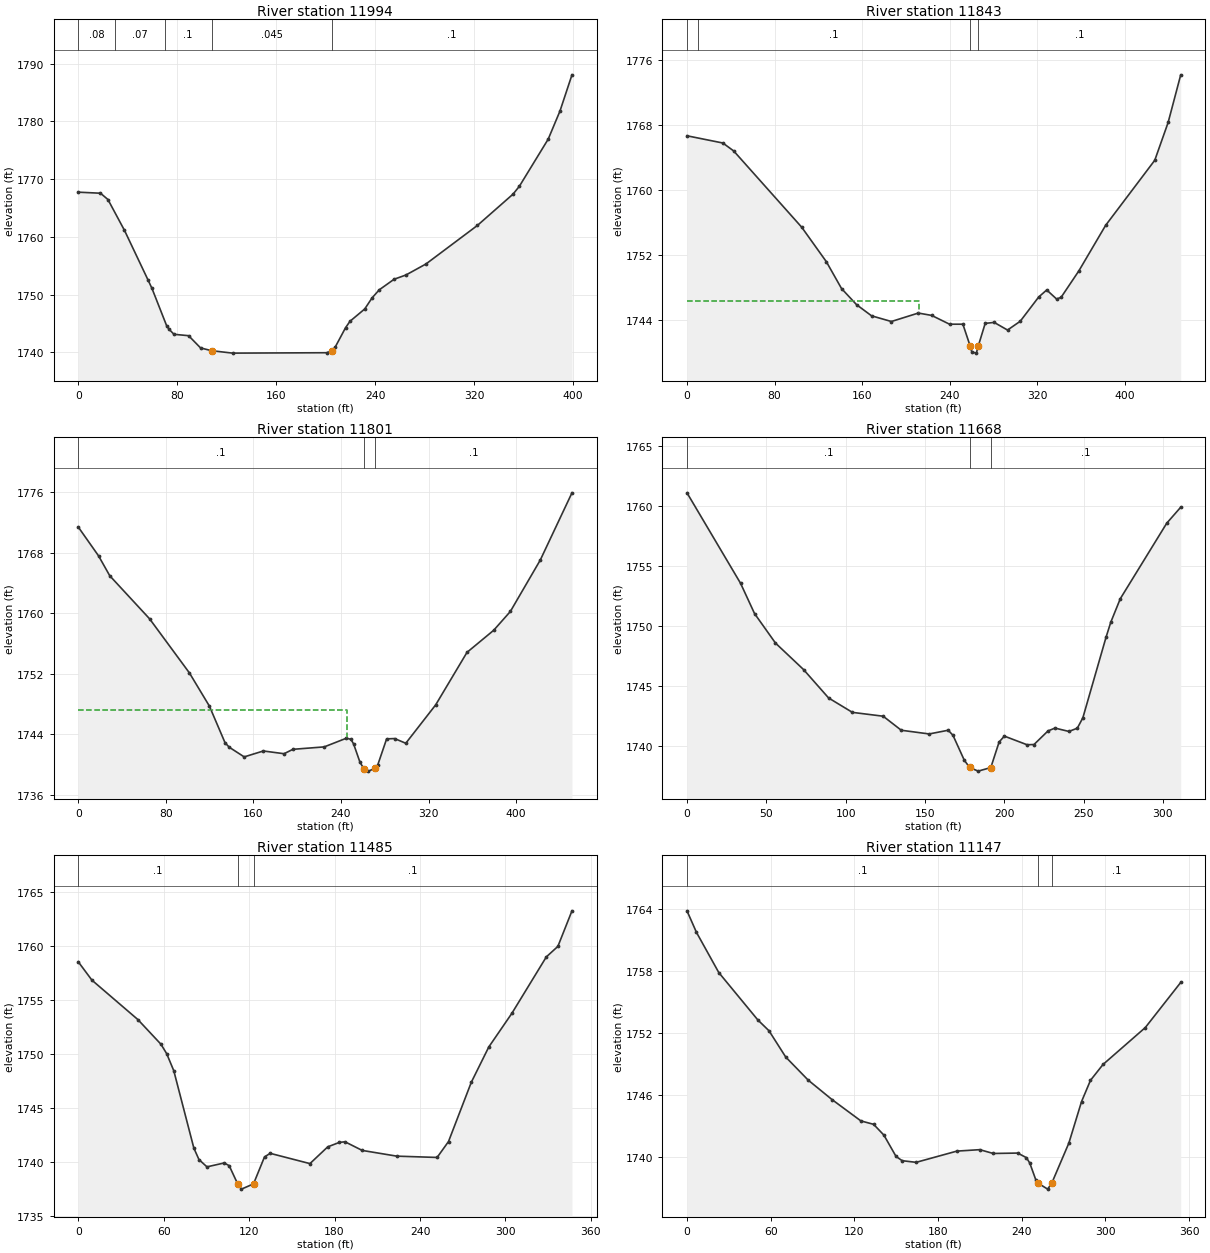
Type RM Length L Ch R = 1 ,11994   ,150.9,150.9,150.9
XS GIS Cut Line= 2
2212220.58325988721469.0113452342212515.28838691721738.089939476
#Sta/Elev= 30
       0 1767.72      18 1767.54      24 1766.45    37.4  1761.1    56.5 1752.48
    59.6 1751.06    71.4 1744.63    73.4 1743.99    77.4 1743.11    89.2 1742.87
    98.9 1740.75   107.8 1740.27   124.8 1739.85   200.9 1739.92   205.3 1740.28
   207.9 1740.97   216.1 1744.26   219.7 1745.37   231.6  1747.5   237.5 1749.41
   243.3 1750.81   255.3 1752.64   264.9 1753.38   281.1 1755.29   322.6 1761.95
   351.5 1767.39   356.6 1768.75   379.9 1776.91   389.4 1781.77   399.1 1788.04
#Mann= 5 ,-1,0
       0     .08       0      30     .07       0      70      .1       0
   107.8    .045       0   205.3      .1       0
Bank Sta=107.8,205.3
XS Rating Curve= 0 ,0
Exp/Cntr(USF)=0,0
Exp/Cntr=0.3,0.1

Type RM Length L Ch R = 1 ,11843   ,42.9,42.9,42.9
XS GIS Cut Line= 3
2212059.97120797721612.8589998912212224.95434555721702.181080742
2212483.46295601721752.621785223
#Sta/Elev= 30
       0 1766.68    32.8 1765.79    42.7 1764.81   104.8 1755.43   127.3 1751.19
   141.2 1747.88   154.9  1745.9   168.6 1744.53   186.7 1743.83   211.3 1744.87
   223.5 1744.58   239.8  1743.5     252  1743.5   258.8 1740.76   260.2 1740.09
   264.3 1739.94  265.991740.781   272.4  1743.6   280.6 1743.72   292.8 1742.78
   304.4 1743.86   321.3 1746.85   328.6 1747.71   337.6  1746.6   341.7  1746.8
     358 1750.07   382.4 1755.66   427.3 1763.67   439.5 1768.32     451 1774.18
#Mann= 4 ,-1,0
       0     .08       0      10      .1       0   258.8    .045       0
  265.99      .1       0
#XS Ineff= 2 , 0
          211.72 1746.36
Permanent Ineff=
       F       F
Bank Sta=258.8,265.99
XS Rating Curve= 0 ,0
Exp/Cntr(USF)=0,0
Exp/Cntr=0.3,0.1

Type RM Length L Ch R = 1 ,11801   ,132.3,132.3,132.3
XS GIS Cut Line= 3
2212046.83560785721653.3166482772212211.81874542721742.638729128
2212470.32735588721793.079433609
#Sta/Elev= 30
       0  1771.4    18.6 1767.58    28.8 1764.96    65.2 1759.27   101.6 1752.12
   119.8 1747.75   134.1 1742.91     138 1742.31   151.6 1741.04   169.1 1741.82
     188 1741.46   196.1 1742.04   224.7 1742.36     245 1743.51   249.1 1743.36
   251.5 1742.76   257.3 1740.36   260.8 1739.49   265.1 1739.16   270.9 1739.52
   273.6 1739.98   281.7 1743.42     289 1743.46   299.2 1742.84   326.5 1747.91
   355.1 1754.84   379.5 1757.76   394.7 1760.24     422 1767.02     451 1775.91
#Mann= 3 ,-1,0
       0      .1       0   260.8    .045       0   270.9      .1       0
#XS Ineff= 2 , 0
          245.15 1747.25
Permanent Ineff=
       F       F
Bank Sta=260.8,270.9
XS Rating Curve= 0 ,0
Exp/Cntr(USF)=0,0
Exp/Cntr=0.3,0.1

Type RM Length L Ch R = 1 ,11668   ,182.9,182.9,182.9
XS GIS Cut Line= 2
2212049.46272787721789.4014655732212332.14084257721919.706618815
#Sta/Elev= 30
       0 1761.12    33.8 1753.57    42.6 1751.05    55.8 1748.59    73.5 1746.38
    89.3 1744.01   104.3 1742.81   123.7 1742.49   135.1 1741.32   152.7 1741.01
   164.7 1741.32   167.7  1740.9   174.8 1738.83  178.211738.213   183.6 1737.91
  191.561738.208   196.8 1740.34   200.1 1740.83   214.4 1740.11   218.8 1740.13
   227.6 1741.26     232  1741.5   240.8 1741.22   246.1 1741.49   249.6 1742.36
   264.2 1749.07   267.2 1750.33   273.2 1752.29   302.5 1758.59   311.3 1759.92
#Mann= 3 ,-1,0
       0      .1       0  178.21    .045       0  191.56      .1       0
Bank Sta=178.21,191.56
XS Rating Curve= 0 ,0
Exp/Cntr(USF)=0,0
Exp/Cntr=0.3,0.1

Type RM Length L Ch R = 1 ,11485   ,338.5,338.4,338.5
XS GIS Cut Line= 2
2211990.66843038721995.4065958322212333.98047526721947.172672173
#Sta/Elev= 30
       0 1758.55     9.6 1756.85    41.9  1753.2    58.1 1750.92    62.1 1750.05
    67.1 1748.47    81.2 1741.31    84.8 1740.25    90.4 1739.58   102.5 1739.94
     106 1739.69   111.9 1738.02   114.6 1737.52  123.081738.005   130.8  1740.5
   134.8 1740.83   162.7 1739.88   175.2 1741.43   183.3 1741.84   187.3  1741.9
   199.4  1741.1   223.7 1740.57     252 1740.45     260 1741.92     276  1747.4
   288.3 1750.67   304.5 1753.78   328.7    1759   336.8 1759.97   346.7 1763.26
#Mann= 3 ,-1,0
       0      .1       0   111.9    .045       0  123.08      .1       0
Bank Sta=111.9,123.08
XS Rating Curve= 0 ,0
Exp/Cntr(USF)=0,0
Exp/Cntr=0.3,0.1

Type RM Length L Ch R = 1 ,11147   ,230.6,230.8,230.6
XS GIS Cut Line= 3
2211973.40212836722064.7989095612212086.29196411722059.677091914
 2212307.4991054722155.240578156
#Sta/Elev= 30
       0 1763.86     6.8 1761.77    22.8 1757.87    50.8 1753.27    58.8 1752.22
    70.8 1749.67    86.9 1747.43     104 1745.54   124.7 1743.47   133.8 1743.14
   141.2 1742.09   149.9 1740.02   154.3 1739.61   164.3 1739.45   193.5 1740.54
   209.9 1740.68   219.6 1740.31   237.1 1740.35   243.4  1739.9   245.8 1739.37
   250.1 1737.75     2521737.403   258.6 1736.85   261.6 1737.45   273.8 1741.32
   282.9 1745.35   289.3 1747.41   298.3 1748.95   328.6 1752.53     354 1756.91
#Mann= 3 ,-1,0
       0      .1       0     252    .045       0   261.6      .1       0
Bank Sta=252,261.6
XS Rating Curve= 0 ,0
Exp/Cntr(USF)=0,0
Exp/Cntr=0.3,0.1