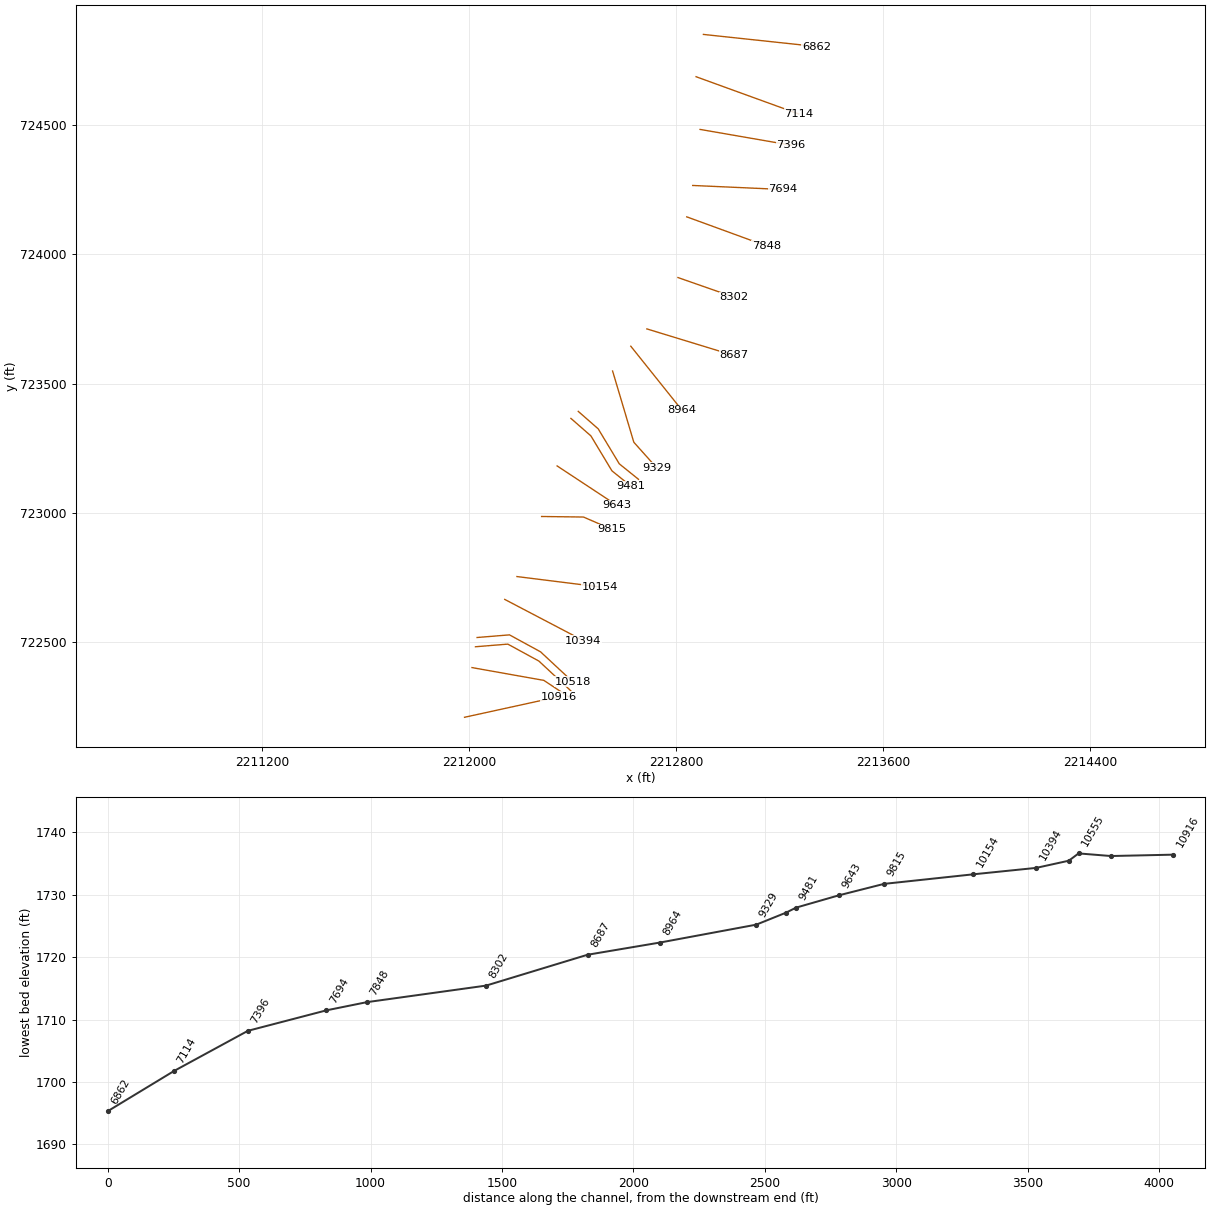
HEC-RAS study LILAURELFK.prj: LILAURELFK

--- LILAURELFK.g01 (geometry) --- (continued)

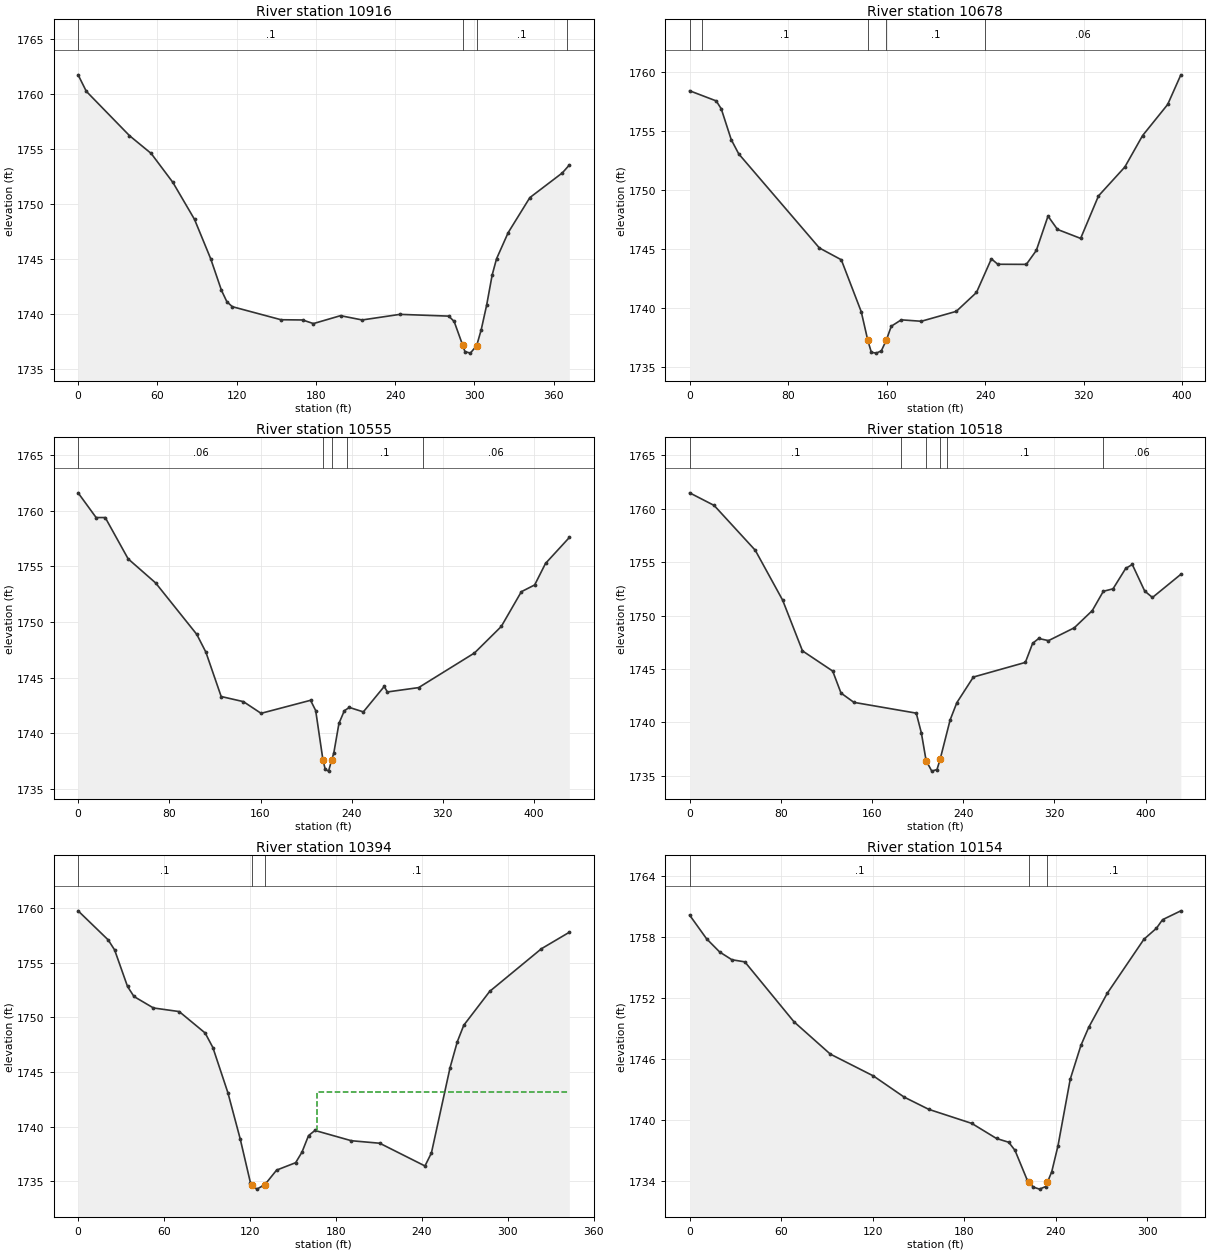
Type RM Length L Ch R = 1 ,10916   ,229.1,237.9,229.1
XS GIS Cut Line= 2
 2211982.1565615722210.0948442782212345.32963376722289.538953835
#Sta/Elev= 30
       0 1761.74     6.2 1760.24    38.9  1756.2    55.3 1754.58    71.7 1751.95
    88.1 1748.58   100.3 1745.01   108.5 1742.12   112.6 1741.08   116.7 1740.63
   153.6 1739.44   169.9 1739.42   178.1 1739.09   198.6 1739.81     215 1739.42
   243.6 1739.93   280.5 1739.77   284.6 1739.29  291.131737.101   292.8 1736.54
   296.9  1736.4  301.691737.093   305.1 1738.53   309.2 1740.76   313.4 1743.52
   316.7 1744.99   325.5 1747.37   341.9 1750.56   366.5 1752.81   371.8 1753.53
#Mann= 4 ,-1,0
       0      .1       0  291.13    .045       0  301.69      .1       0
     370     .06       0
Bank Sta=291.13,301.69
XS Rating Curve= 0 ,0
Exp/Cntr(USF)=0,0
Exp/Cntr=0.3,0.1

Type RM Length L Ch R = 1 ,10678   ,132.7,122.9,132.7
XS GIS Cut Line= 3
2212010.89533191722402.1821348222212288.79469721722352.706630349
2212386.04807149 722288.21837907
#Sta/Elev= 30
       0 1758.41    21.6 1757.55    25.7 1756.88    33.8 1754.27    39.9 1753.06
   105.4 1745.09   123.2 1744.09   139.4 1739.69  144.73 1737.26   147.6 1736.25
   151.6 1736.18   155.7 1736.37   159.8 1737.29   163.8 1738.46   171.9    1739
   188.2 1738.88   216.6 1739.72     233 1741.32   245.1 1744.17   250.3 1743.71
   273.5  1743.7   281.6 1744.88   291.1 1747.79   298.8 1746.66   317.6  1745.9
   332.1  1749.5   353.5 1751.95   367.9 1754.61   388.3 1757.25     399 1759.76
#Mann= 5 ,-1,0
       0     .06       0      10      .1       0  144.73    .045       0
   159.8      .1       0     240     .06       0
Bank Sta=144.73,159.8
XS Rating Curve= 0 ,0
Exp/Cntr(USF)=0,0
Exp/Cntr=0.3,0.1

Type RM Length L Ch R = 1 ,10555   ,37.3,37.3,37.3
XS GIS Cut Line= 4
2212024.40765716722482.6941589472212149.53212971722492.908401604
2212269.54948094722427.3670112192212392.97157971722312.456781324
#Sta/Elev= 30
       0 1761.59    15.8 1759.37    23.8 1759.37    43.9 1755.66      68  1753.5
   104.1 1748.88   112.1 1747.28   125.5  1743.3     145 1742.84   160.5 1741.79
   203.9 1742.96   208.4 1742.04  214.751737.619   216.8 1736.75   219.7  1736.6
  222.521737.636   224.3 1738.23   228.8 1740.88   233.5 1742.02   237.9 1742.32
   250.2 1741.92   268.5  1744.2   271.3 1743.71   298.7  1744.1   347.7 1747.21
   371.2 1749.59   388.8 1752.71   400.5 1753.32     410 1755.25   430.9 1757.58
#Mann= 5 ,-1,0
       0     .06       0  214.75    .045       0  222.52     .06       0
  235.54      .1       0  302.29     .06       0
Bank Sta=214.75,222.52
XS Rating Curve= 0 ,0
Exp/Cntr(USF)=0,0
Exp/Cntr=0.3,0.1

Type RM Length L Ch R = 1 ,10518   ,124.2,124.2,124.2
XS GIS Cut Line= 4
2212030.79155882722518.4440082472212155.91603137722528.658250905
 2212275.9333826 722463.116860522212399.35548137722348.206630625
#Sta/Elev= 30
       0 1761.49    21.5 1760.31    57.6 1756.11    81.6 1751.44      99 1746.69
   125.5  1744.8   132.8 1742.74   144.1 1741.87   198.8 1740.86   203.3    1739
  207.431736.425   212.4 1735.43     217 1735.58   219.7 1736.52   228.5 1740.22
   234.4 1741.84   248.9 1744.24   294.5 1745.61   300.9  1747.4   306.2 1747.85
   314.8 1747.65   337.4 1748.85   353.2 1750.46   362.9 1752.27   371.4  1752.5
   382.5 1754.41   388.3 1754.78   399.2 1752.29     406 1751.69   430.9 1753.86
#Mann= 6 ,-1,0
       0      .1       0  185.54     .06       0  207.43    .045       0
   219.7     .06       0  225.54      .1       0  362.29     .06       0
Bank Sta=207.43,219.7
XS Rating Curve= 0 ,0
Exp/Cntr(USF)=0,0
Exp/Cntr=0.3,0.1

Type RM Length L Ch R = 1 ,10394   ,239.5,239.5,239.5
XS GIS Cut Line= 2
2212137.61551328722665.6993398912212441.48923233722506.527391814
#Sta/Elev= 30
       0 1759.75      21 1757.09    25.5 1756.17    34.5 1752.83      39 1751.91
    52.6 1750.86    70.6 1750.53    88.7 1748.57    94.1 1747.24   104.6  1743.1
   113.2 1738.87   120.3 1734.88  121.141734.696   124.8 1734.28   130.4 1734.69
   138.6 1736.02   151.9  1736.7   156.3 1737.66   160.9 1739.18   165.4 1739.65
   190.8 1738.71   210.6 1738.48   242.2  1736.4   246.7 1737.59   259.7 1745.39
   264.8 1747.78   269.3 1749.28   287.4 1752.38   323.5 1756.28     343 1757.79
#Mann= 3 ,-1,0
       0      .1       0  121.14    .045       0   130.4      .1       0
#XS Ineff= 2 , 0
                          167.07         1743.18
Permanent Ineff=
       F       F
Bank Sta=121.14,130.4
XS Rating Curve= 0 ,0
Exp/Cntr(USF)=0,0
Exp/Cntr=0.3,0.1

Type RM Length L Ch R = 1 ,10154   ,338.9,339.1,338.9
XS GIS Cut Line= 2
2212184.67032493722754.0313460552212504.12811997722714.099121674
#Sta/Elev= 30
       0 1760.14    11.1 1757.82    19.7 1756.52    27.7 1755.76    36.2 1755.55
    68.4 1749.67    92.2  1746.5   120.4 1744.36   140.6 1742.28   156.7 1741.08
   184.9  1739.7   201.1 1738.22   209.1 1737.85   213.2 1737.06   221.2 1734.15
   222.5 1733.91   225.2 1733.45   229.3 1733.25   233.3  1733.5  234.451733.914
   237.3 1734.96   241.4 1737.51   249.4 1744.03   256.4 1747.35   261.5 1749.12
   273.6 1752.45   297.7 1757.77   305.9 1758.85   309.9 1759.69   321.9 1760.56
#Mann= 3 ,-1,0
       0      .1       0   222.5    .045       0  234.45      .1       0
Bank Sta=222.5,234.45
XS Rating Curve= 0 ,0
Exp/Cntr(USF)=0,0
Exp/Cntr=0.3,0.1

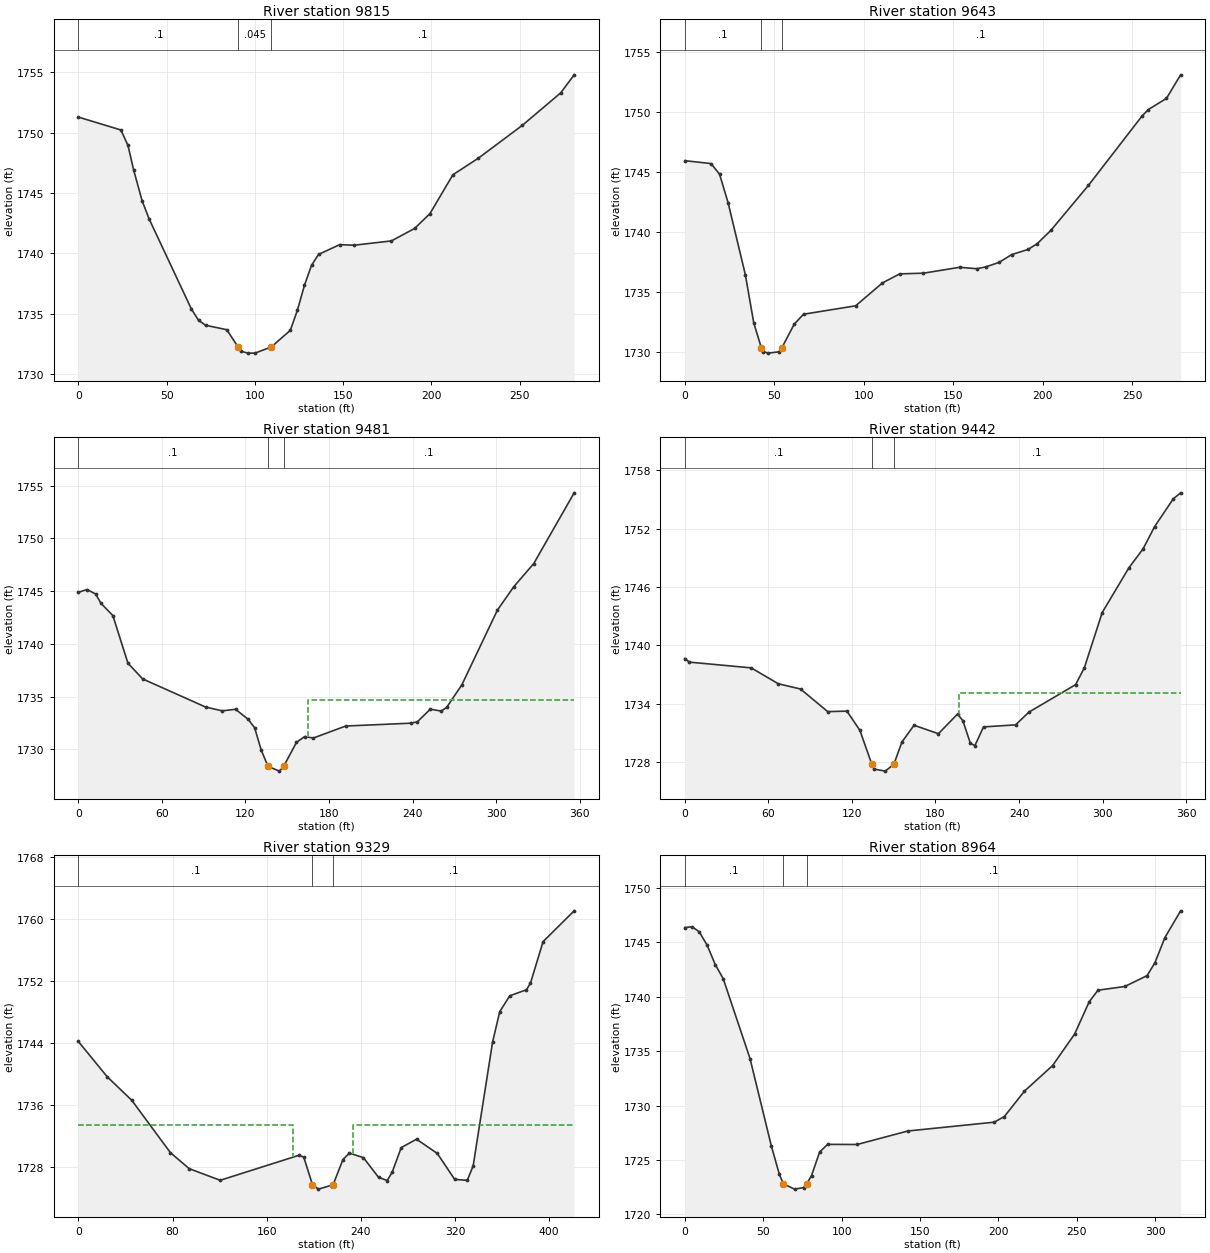
Type RM Length L Ch R = 1 ,9815    ,171.9,172.4,171.9
XS GIS Cut Line= 3
2212280.08991892722986.2298359712212441.92051247722984.128139951
2212551.20870551  722936.8399795
#Sta/Elev= 30
       0 1751.28    24.1 1750.21    28.1 1748.94    31.4 1746.86    36.1 1744.36
    40.1 1742.84    64.1 1735.36    68.1 1734.44    72.1 1734.03    84.1 1733.66
   90.591732.209    92.1 1731.88    96.1 1731.72   100.1 1731.72  109.331732.234
   120.1 1733.61   124.1 1735.27   128.1 1737.34   132.1 1738.99   136.1  1739.9
   148.1 1740.71   156.1 1740.66   177.4 1741.02   190.5 1742.05   199.2 1743.28
   212.2  1746.5   226.6 1747.87   251.5 1750.59   273.3 1753.29   280.9 1754.78
#Mann= 3 ,-1,0
       0      .1       0   90.59    .045       0  109.33      .1       0
Bank Sta=90.59,109.33
XS Rating Curve= 0 ,0
Exp/Cntr(USF)=0,0
Exp/Cntr=0.3,0.1

Type RM Length L Ch R = 1 ,9643    ,161.9,161.9,161.9
XS GIS Cut Line= 2
2212339.98825549723181.687565834 2212571.1748177723029.314604381
#Sta/Elev= 30
       0 1745.91    14.6 1745.67    19.4 1744.79    24.2  1742.4    33.8 1736.42
    38.5 1732.41    42.81730.292    43.8 1730.01    46.7 1729.88    52.5 1729.99
   54.061730.286    61.1 1732.29    66.3 1733.12    95.4 1733.82   110.4 1735.73
     120 1736.48   133.3 1736.54   153.5 1737.03   163.1 1736.91     168 1737.06
   175.4 1737.43   182.6 1738.09   191.8 1738.52   196.9 1739.01   204.4  1740.1
   225.4 1743.85   255.3 1749.62   258.9 1750.17     269  1751.1   276.9 1753.06
#Mann= 3 ,-1,0
       0      .1       0    42.8    .045       0   54.06      .1       0
Bank Sta=42.8,54.06
XS Rating Curve= 0 ,0
Exp/Cntr(USF)=0,0
Exp/Cntr=0.3,0.1

Type RM Length L Ch R = 1 ,9481    ,39.1,39.1,39.1
XS GIS Cut Line= 4
 2212393.3886734 723365.335655592212470.60834789723297.768440412
2212551.96479065723162.6340100552212626.42661962 723102.65087005
#Sta/Elev= 30
       0 1744.89     6.3 1745.15    12.4 1744.73    16.3 1743.84    24.8 1742.68
    35.6 1738.17    46.2 1736.67    91.4    1734   103.3 1733.64   112.9 1733.79
     122 1732.83   126.6 1732.03   131.3 1729.92   136.2 1728.37   144.4 1727.92
  147.421728.374   156.6 1730.65   162.5  1731.2   168.7 1731.06     192  1732.2
   238.7 1732.47   243.4  1732.6   252.7  1733.8   260.6 1733.62   264.4 1733.96
   275.4 1736.12   300.9  1743.2   312.7 1745.43     327 1747.62     356 1754.33
#Mann= 3 ,-1,0
       0      .1       0   136.2    .045       0  147.42      .1       0
#XS Ineff= 2 , 0
                          164.77         1734.67
Permanent Ineff=
       F       F
Bank Sta=136.2,147.42
XS Rating Curve= 0 ,0
Exp/Cntr(USF)=0,0
Exp/Cntr=0.3,0.1

Type RM Length L Ch R = 1 ,9442    ,112.6,112.6,112.6
XS GIS Cut Line= 4
2212421.65658995723392.5693800752212498.87626444723325.002164897
2212580.23270721 723189.867734542212654.69453618723129.884594535
#Sta/Elev= 30
       0 1738.66     3.3 1738.29    47.7  1737.7    67.1 1736.07    83.1 1735.53
   102.6 1733.21   116.4 1733.26   125.7 1731.29  134.331727.789   136.1 1727.31
   143.9  1727.1   150.1  1727.8   155.9 1730.09   164.6 1731.81   182.1 1730.94
   195.8 1732.96   199.6 1732.29   205.1 1729.94   208.3 1729.73   214.5 1731.64
   237.5 1731.85   247.1 1733.16   280.6 1735.98   286.9 1737.72   299.7 1743.38
   318.8 1747.96   329.1 1749.93   337.3  1752.2   350.7 1755.05     356 1755.67
#Mann= 3 ,-1,0
       0      .1       0  134.33    .045       0   150.1      .1       0
#XS Ineff= 2 , 0
                          196.69         1735.15
Permanent Ineff=
       F       F
Bank Sta=134.33,150.1
XS Rating Curve= 0 ,0
Exp/Cntr(USF)=0,0
Exp/Cntr=0.3,0.1

Type RM Length L Ch R = 1 ,9329    ,365.6,365.6,365.6
XS GIS Cut Line= 3
2212554.46423264723548.6747960322212636.43037742723273.352617408
2212725.75245827723173.522056456
#Sta/Elev= 30
       0 1744.24    24.5 1739.69    45.4 1736.65    78.2  1729.9    94.2 1727.83
   120.5 1726.33   187.5 1729.56   191.5 1729.32  198.921725.754     204 1725.19
   216.4 1725.75   224.8 1729.01   230.3 1729.84   242.2 1729.25     255 1726.72
   262.4  1726.3   266.6 1727.37   274.3 1730.55   287.3 1731.63   304.9  1729.8
   319.7 1726.45   330.4 1726.32   335.4 1728.19   351.9 1744.16     358 1748.09
   366.5 1750.13   380.7 1750.91   384.1 1751.77   394.8 1757.12   421.2 1761.09
#Mann= 3 ,-1,0
       0      .1       0  198.92    .045       0   216.4      .1       0
#XS Ineff= 2 , 0
          182.07 1733.51  232.93         1733.46
Permanent Ineff=
       F       F
Bank Sta=198.92,216.4
XS Rating Curve= 0 ,0
Exp/Cntr(USF)=0,0
Exp/Cntr=0.3,0.1

Type RM Length L Ch R = 1 ,8964    ,276.2,276.2,276.2
XS GIS Cut Line= 2
2212624.87104931723644.301964943 2212822.4304752 723397.35268259
#Sta/Elev= 30
       0 1746.35     4.6 1746.43     9.1 1745.98    14.2 1744.75    19.4 1742.96
    24.5 1741.66    41.6 1734.32    55.2 1726.29    60.3 1723.69    62.9 1722.81
      70 1722.33    75.7 1722.47   77.781722.829    80.8 1723.57      86 1725.74
    91.1 1726.44   109.9 1726.43   142.3 1727.67   197.4 1728.48   203.8    1729
   216.6 1731.33   234.5 1733.67   248.6 1736.57   257.9 1739.54   263.5  1740.6
   280.6 1740.94   294.8 1741.94   299.8 1743.12   306.2 1745.44   316.2 1747.89
#Mann= 3 ,-1,0
       0      .1       0    62.9    .045       0   77.78      .1       0
Bank Sta=62.9,77.78
XS Rating Curve= 0 ,0
Exp/Cntr(USF)=0,0
Exp/Cntr=0.3,0.1

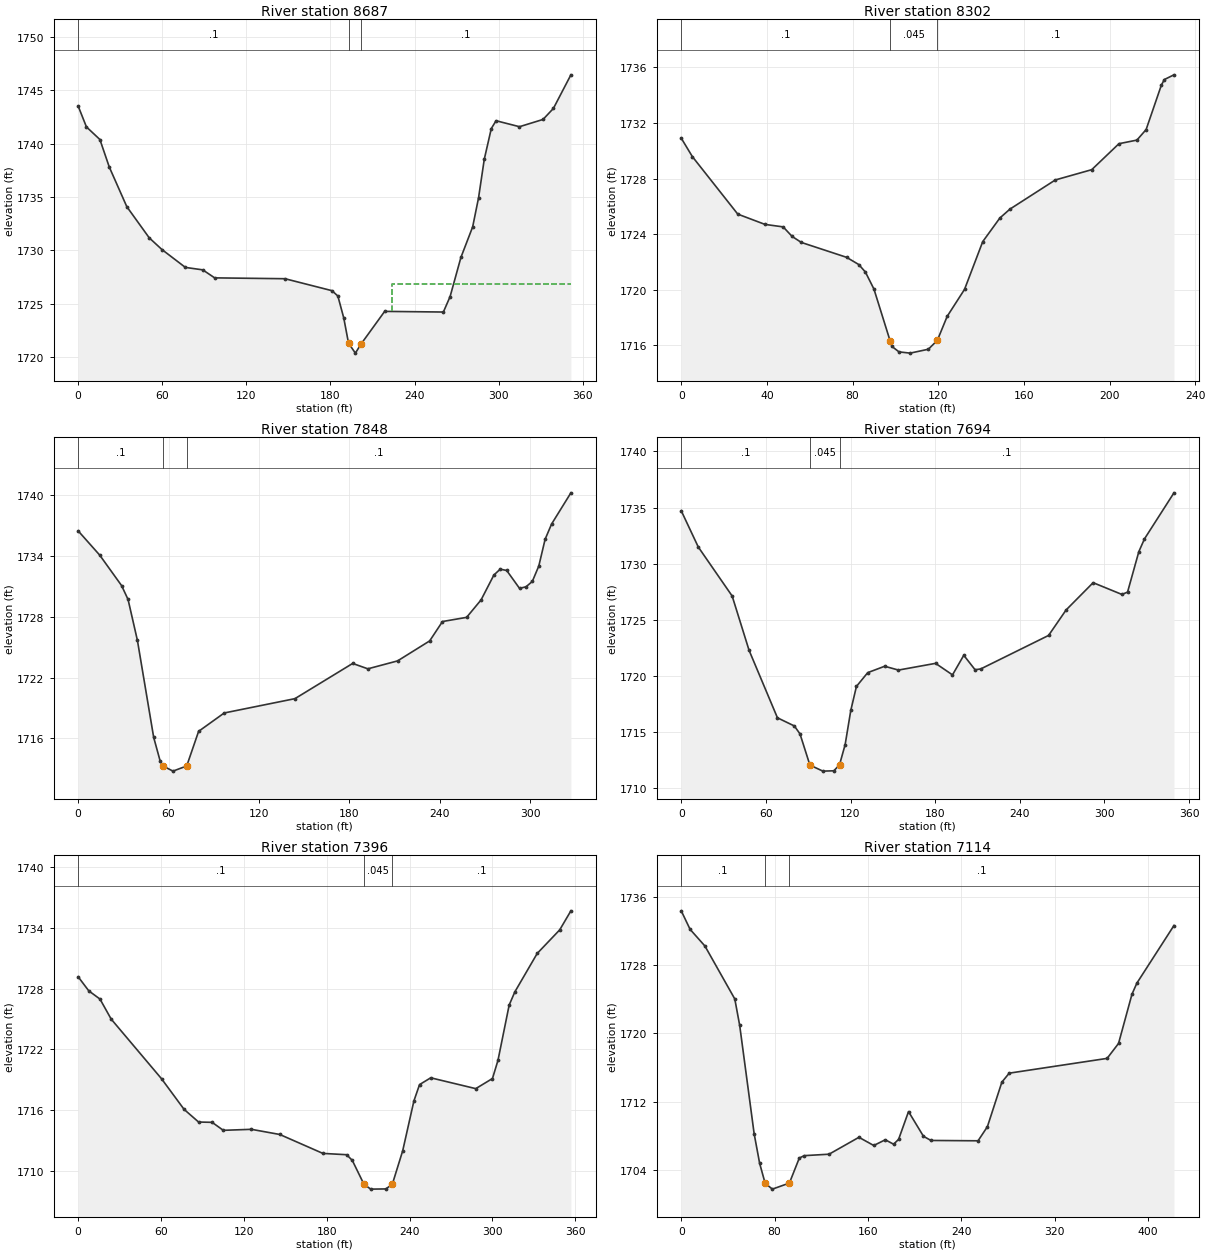
Type RM Length L Ch R = 1 ,8687    ,385.9,385.9,385.9
XS GIS Cut Line= 2
2212686.98784279723711.322715804  2213023.259206723608.573132603
#Sta/Elev= 30
       0 1743.51     5.9 1741.56    15.5 1740.38    22.2  1737.8    34.7 1734.09
    50.7 1731.17    59.8 1730.07    76.5  1728.4    88.9 1728.17    97.4 1727.42
   147.6 1727.34   181.1 1726.22   185.3 1725.72   189.5 1723.67  192.921721.301
   197.8 1720.37     202 1721.25   218.7 1724.28   260.6 1724.22   265.4 1725.67
   273.1 1729.33   281.5  1732.2   285.7 1734.92   289.8 1738.54   294.8 1741.41
   298.2 1742.14   314.9 1741.58   331.7 1742.26   339.1 1743.29   351.6 1746.44
#Mann= 3 ,-1,0
       0      .1       0  192.92    .045       0     202      .1       0
#XS Ineff= 2 , 0
                          223.98         1726.86
Permanent Ineff=
       F       F
Bank Sta=192.92,202
XS Rating Curve= 0 ,0
Exp/Cntr(USF)=0,0
Exp/Cntr=0.3,0.1

Type RM Length L Ch R = 1 ,8302    ,448.4,453.4,450.1
XS GIS Cut Line= 2
 2212807.2515595723909.816228807 2213024.4268149723833.921650306
#Sta/Elev= 30
       0 1730.91     5.2 1729.58    26.4 1725.44    39.1  1724.7    47.6 1724.52
    51.8 1723.83    56.1  1723.4    77.2 1722.33    82.9 1721.81      86 1721.27
      90 1720.04   97.511716.328    98.4 1715.91   101.7 1715.52   106.9 1715.43
   115.4 1715.71   119.6 1716.35   124.2 1718.08   132.3 1720.02   140.8 1723.46
   148.8 1725.16   153.5  1725.8   174.7  1727.9   191.7 1728.64   204.4 1730.51
   212.8 1730.77   217.1 1731.53   224.2 1734.72   225.6 1735.13   230.1 1735.47
#Mann= 3 ,-1,0
       0      .1       0   97.51    .045       0   119.6      .1       0
Bank Sta=97.51,119.6
XS Rating Curve= 0 ,0
Exp/Cntr(USF)=0,0
Exp/Cntr=0.3,0.1

Type RM Length L Ch R = 1 ,7848    ,149.8,153.7,159.9
XS GIS Cut Line= 2
 2212841.1122176 724144.50561771 2213148.1933583724032.415163309
#Sta/Elev= 30
       0 1736.45    14.3 1734.06    28.8 1731.06    33.1 1729.69    39.3 1725.66
    50.1  1716.1    54.4 1713.77   56.341713.283    62.9 1712.78   72.011713.289
    79.9  1716.7    96.9 1718.51   143.8 1719.92   182.1 1723.39   192.2 1722.86
   211.9 1723.64   233.2 1725.61   241.7 1727.52   257.7 1727.93   267.3 1729.65
   275.8  1732.1     280 1732.68   284.3 1732.55   292.8 1730.79   297.1 1730.94
   301.3 1731.47   305.6 1732.99   309.8 1735.63   314.1 1737.13   326.9  1740.2
#Mann= 3 ,-1,0
       0      .1       0   56.34    .045       0   72.01      .1       0
Bank Sta=56.34,72.01
XS Rating Curve= 0 ,0
Exp/Cntr(USF)=0,0
Exp/Cntr=0.3,0.1

Type RM Length L Ch R = 1 ,7694    ,297.4,298.8,291.3
XS GIS Cut Line= 2
2212864.07519263 724265.807208992213213.06051941724250.239090323
#Sta/Elev= 30
       0 1734.71    12.1 1731.47    36.1  1727.1    48.1 1722.25    68.2 1716.23
    80.2  1715.5    84.2 1714.79   91.211712.009   100.4 1711.47   108.2  1711.5
   112.2 1712.03   116.2 1713.84   120.2 1716.89   124.2 1719.03   132.2 1720.26
   144.2 1720.83     154 1720.49   180.3 1721.09   192.3 1720.06   200.3 1721.81
   208.3 1720.52   212.3 1720.59   260.4 1723.58   272.8 1725.85     292 1728.29
   312.4 1727.24   316.4 1727.45   324.4 1731.06   328.4  1732.2   349.3 1736.31
#Mann= 3 ,-1,0
       0      .1       0   91.21    .045       0   112.2      .1       0
Bank Sta=91.21,112.2
XS Rating Curve= 0 ,0
Exp/Cntr(USF)=0,0
Exp/Cntr=0.3,0.1

Type RM Length L Ch R = 1 ,7396    ,279.3,281.3,272
XS GIS Cut Line= 2
2212892.61674352724482.4635271042213244.19675675724421.488395659
#Sta/Elev= 30
       0 1729.17     7.7 1727.78    15.8 1726.97    23.9 1724.99    60.4 1719.09
    76.7 1716.07    87.2 1714.82      97 1714.79   105.1    1714   125.4  1714.1
     146 1713.59   177.2 1711.72   194.4 1711.59   198.5 1711.03  206.871708.689
   211.8 1708.19   222.8 1708.21  227.481708.672     235 1711.98   243.1  1716.9
   247.2 1718.52   255.3 1719.19   287.9 1718.12     300 1719.12     304 1720.92
   312.1 1726.38   316.2 1727.68   332.4 1731.48   348.7 1733.81   356.8 1735.69
#Mann= 3 ,-1,0
       0      .1       0  206.87    .045       0  227.48      .1       0
Bank Sta=206.87,227.48
XS Rating Curve= 0 ,0
Exp/Cntr(USF)=0,0
Exp/Cntr=0.3,0.1

Type RM Length L Ch R = 1 ,7114    ,246.2,252.3,248.6
XS GIS Cut Line= 2
2212877.04862485724686.1464129962213274.03565086724542.141315327
#Sta/Elev= 30
       0 1734.34     7.6 1732.17    20.3 1730.22    45.9 1724.02    50.1 1720.92
    62.5 1708.23    67.2 1704.77    71.9 1702.44    78.1 1701.75    92.7 1702.46
   101.2 1705.39   105.4 1705.67   126.7 1705.84   152.3 1707.82     165 1706.86
   174.9 1707.53     182 1707.01   186.3 1707.58   194.8 1710.83   207.6 1707.94
     214 1707.45   254.4 1707.41   262.4 1709.06   274.8 1714.28   281.1 1715.33
     365 1717.06   374.8 1718.81   386.3 1724.57   390.5 1725.87   422.3 1732.62
#Mann= 3 ,-1,0
       0      .1       0    71.9    .045       0    92.7      .1       0
Bank Sta=71.9,92.7
XS Rating Curve= 0 ,0
Exp/Cntr(USF)=0,0
Exp/Cntr=0.3,0.1

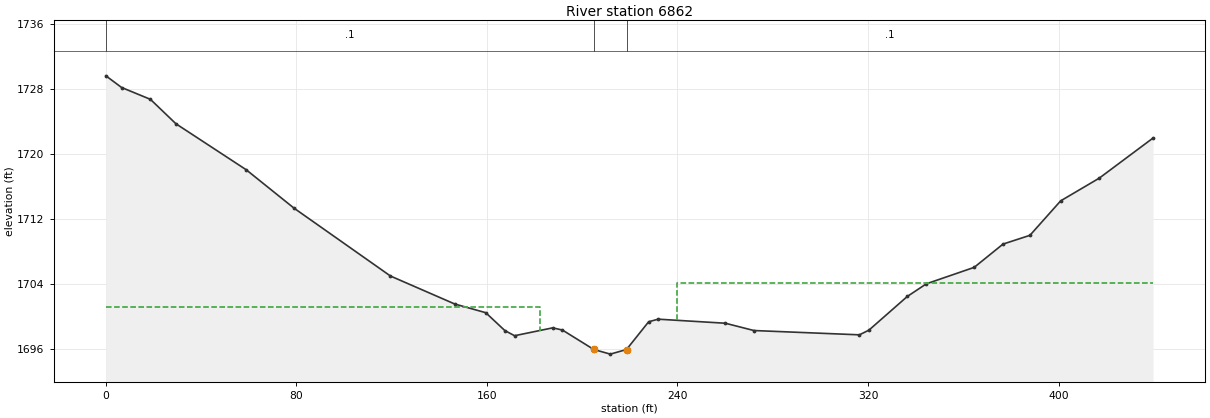
Type RM Length L Ch R = 1 ,6862    ,189.8,198.1,198.7
XS GIS Cut Line= 2
2212905.59017574724849.6116589982213342.79484164724802.907302998
#Sta/Elev= 30
       0 1729.63     6.6 1728.19    18.7 1726.73    29.4 1723.72    58.9 1718.05
      79 1713.31   119.5 1704.94   146.5 1701.49   159.5 1700.42   167.5 1698.22
   171.6 1697.58   187.6 1698.55   191.7 1698.28  204.841695.886   211.8 1695.31
   218.6 1695.88   227.9  1699.3   231.9 1699.62   260.1 1699.12   272.1 1698.22
   316.4 1697.69   320.4 1698.27   336.5 1702.42   344.5 1703.98   364.6 1706.01
   376.7 1708.88     388 1709.96   400.9 1714.21   417.1 1717.01   439.7 1721.96
#Mann= 3 ,-1,0
       0      .1       0  204.84    .045       0   218.6      .1       0
#XS Ineff= 2 , 0
          182.07 1701.14  239.82         1704.12
Permanent Ineff=
       F       F
Bank Sta=204.84,218.6
XS Rating Curve= 0 ,0
Exp/Cntr(USF)=0,0
Exp/Cntr=0.3,0.1