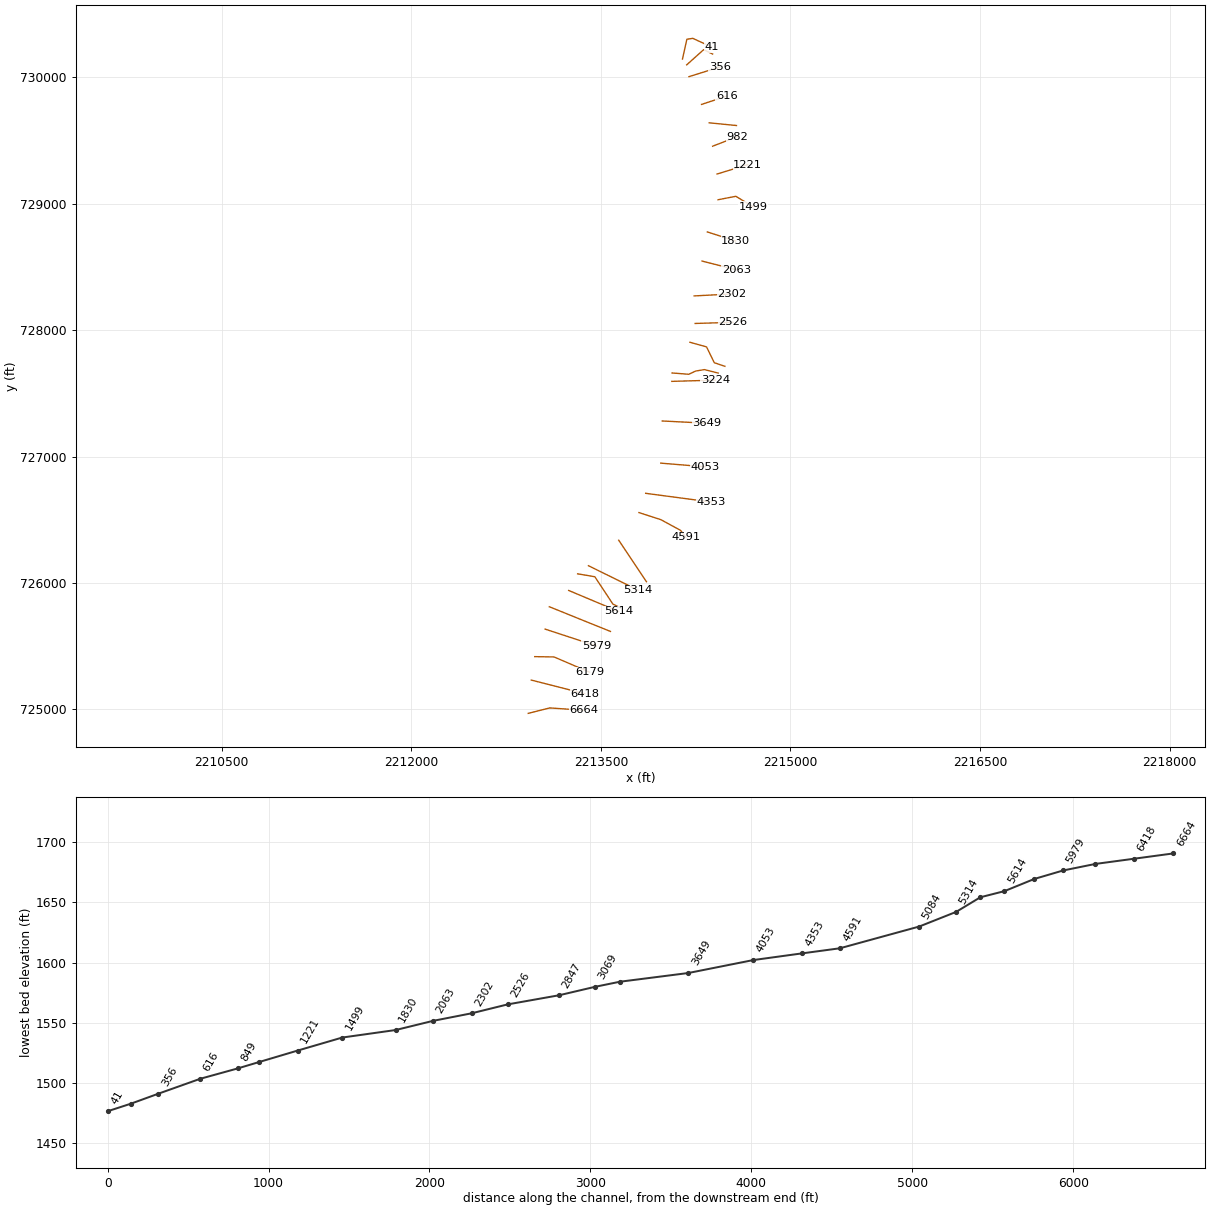
HEC-RAS study LILAURELFK.prj: LILAURELFK

--- LILAURELFK.g01 (geometry) --- (continued)

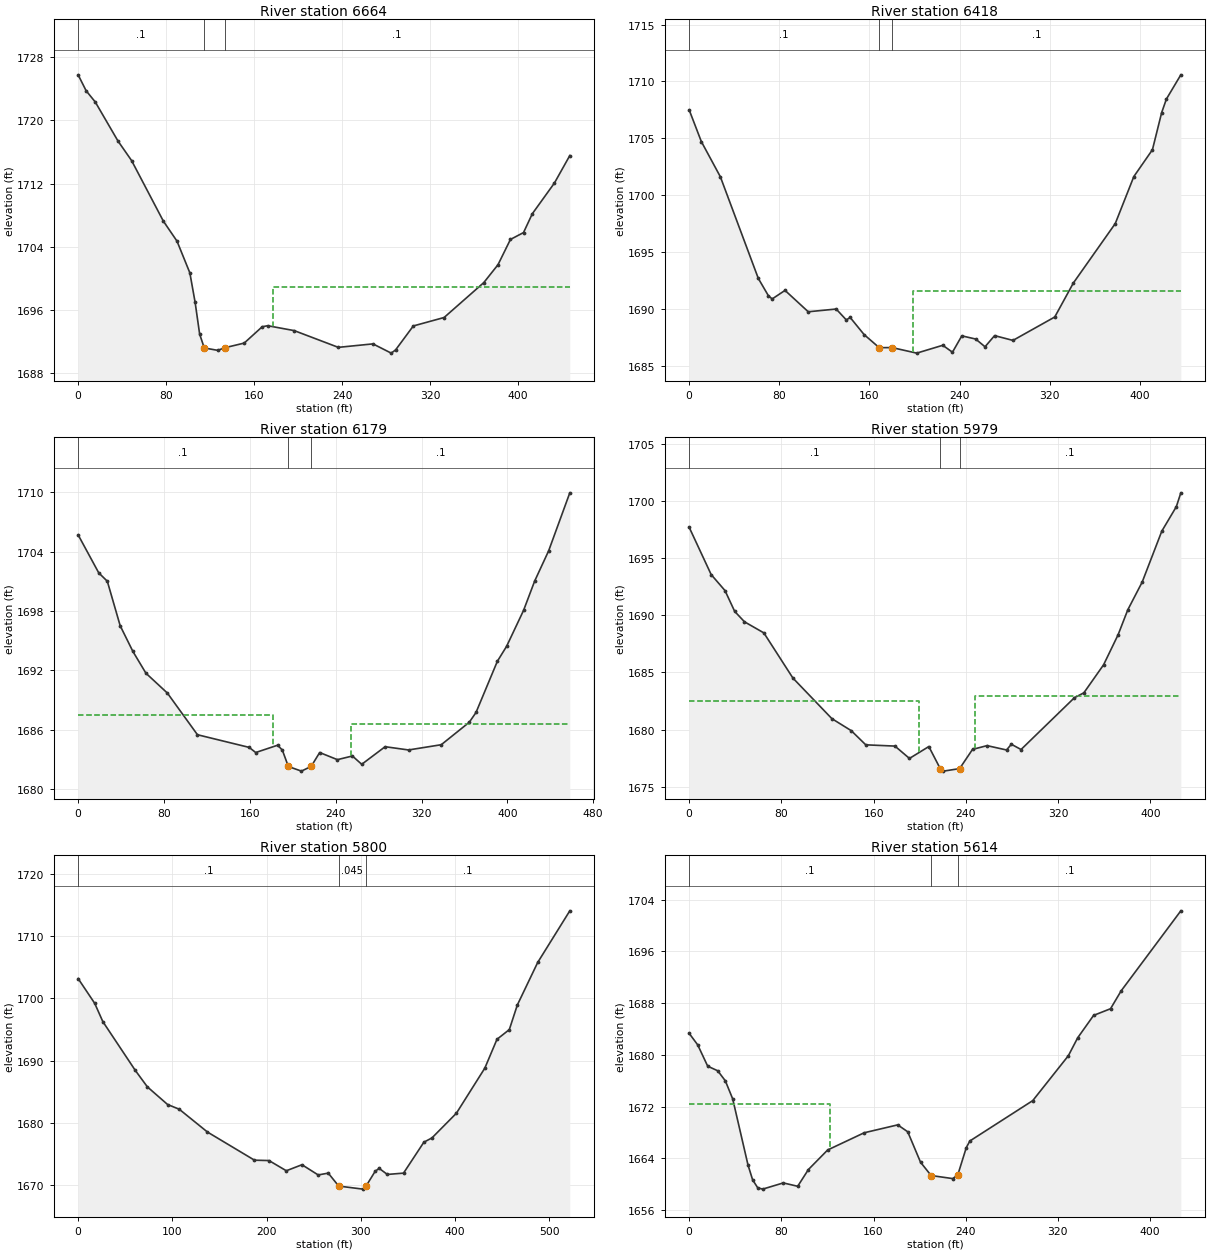
Type RM Length L Ch R = 1 ,6664    ,251.3,246.4,236.3
XS GIS Cut Line= 3
2212925.05032408724968.9672354452213095.59298595725012.023571265
2213366.14701964724993.616756667
#Sta/Elev= 30
       0 1725.76     7.3 1723.74    15.6 1722.32    36.2 1717.39    48.6 1714.91
    77.5 1707.24    89.9 1704.71   101.6 1700.69   106.4 1696.95   110.5 1692.94
   114.71691.185     127 1690.88   133.21691.205     151  1691.8   167.4 1693.87
   172.4    1694   196.5 1693.38   236.6 1691.26   268.1  1691.7   284.7 1690.53
   288.7 1690.94   304.8 1693.97   332.8 1695.04   368.9 1699.46   381.8 1701.72
   393.1 1704.92     405 1705.79     413 1708.17   433.1 1712.06   447.1 1715.54
#Mann= 3 ,-1,0
       0      .1       0   114.7    .045       0   133.2      .1       0
#XS Ineff= 2 , 0
                          177.12         1698.88
Permanent Ineff=
       F       F
Bank Sta=114.7,133.2
XS Rating Curve= 0 ,0
Exp/Cntr(USF)=0,0
Exp/Cntr=0.3,0.1

Type RM Length L Ch R = 1 ,6418    ,239,238.8,235.6
XS GIS Cut Line= 2
 2212949.6998453725232.3279095592213372.63373575725124.648422113
#Sta/Elev= 30
       0  1707.5    10.8 1704.71    27.7 1701.61    61.4 1692.66    70.4 1691.13
    73.7 1690.86    85.1 1691.61   105.7 1689.73   130.5 1689.97   139.5 1689.01
   142.9 1689.23   155.3 1687.72  168.751686.568     180 1686.58     202 1686.09
   225.1 1686.78   233.7 1686.17     242 1687.61   254.3 1687.33   262.6 1686.65
   271.1 1687.63   287.4 1687.21   324.5 1689.27     341 1692.26   378.2 1697.49
   394.7 1701.63   411.2 1703.99   419.4 1707.26   423.6 1708.45   436.4 1710.58
#Mann= 3 ,-1,0
       0      .1       0  168.75    .045       0     180      .1       0
#XS Ineff= 2 , 0
                          199.12         1691.54
Permanent Ineff=
       F       F
Bank Sta=168.75,180
XS Rating Curve= 0 ,0
Exp/Cntr(USF)=0,0
Exp/Cntr=0.3,0.1

Type RM Length L Ch R = 1 ,6179    ,198.2,200.4,200.6
XS GIS Cut Line= 3
2212976.94405297 725417.847990342213130.03055319725415.253303895
2213410.25668919725294.600384227
#Sta/Elev= 30
       0 1705.69    19.2 1701.85    27.2    1701    39.2  1696.5      51 1693.91
    63.2  1691.7    83.2 1689.69   111.2 1685.48   159.4  1684.2   165.5 1683.68
   185.9 1684.42   190.3 1683.93   195.9 1682.27   208.1  1681.8   217.2 1682.28
   225.1 1683.68   241.6 1682.96   255.6 1683.33   264.3 1682.49   286.1 1684.27
   307.9 1683.94   338.4 1684.47   364.5 1686.74   370.8 1687.73   390.7 1692.91
   399.3 1694.42   415.1 1698.05   425.5 1701.03   438.5 1704.08   458.2 1709.94
#Mann= 3 ,-1,0
       0      .1       0   195.9    .045       0   217.2      .1       0
#XS Ineff= 2 , 0
          182.07  1687.5  254.68         1686.54
Permanent Ineff=
       F       F
Bank Sta=195.9,217.2
XS Rating Curve= 0 ,0
Exp/Cntr(USF)=0,0
Exp/Cntr=0.3,0.1

Type RM Length L Ch R = 1 ,5979    ,179.4,179,178.9
XS GIS Cut Line= 2
2213058.61260963725635.689535596 2213463.8321593725502.751896773
#Sta/Elev= 30
       0  1697.7    19.1 1693.56    31.1 1692.16    39.5 1690.34      48 1689.43
    64.8 1688.46      90 1684.51   123.8 1680.96   140.6 1679.91   153.2 1678.67
   178.5 1678.56   191.1 1677.48   207.9 1678.52   217.8 1676.59   220.6 1676.37
   234.6 1676.59   245.8 1678.27   258.4  1678.6   275.3 1678.22   279.5 1678.72
   287.9 1678.26   334.2 1682.79   342.4 1683.22   359.5 1685.67   372.1  1688.3
   380.5 1690.48     393 1692.91     410 1697.36   422.6  1699.5   426.5 1700.71
#Mann= 3 ,-1,0
       0      .1       0   217.8    .045       0   234.6      .1       0
#XS Ineff= 2 , 0
          199.12  1682.5  248.07         1682.98
Permanent Ineff=
       F       F
Bank Sta=217.8,234.6
XS Rating Curve= 0 ,0
Exp/Cntr(USF)=0,0
Exp/Cntr=0.3,0.1

Type RM Length L Ch R = 1 ,5800    ,180.8,185.3,179.3
XS GIS Cut Line= 2
2213091.86434438725812.5732480522213575.79650931725617.188871305
#Sta/Elev= 30
       0 1703.18    17.6  1699.2    26.2 1696.27    60.7 1688.42    73.5 1685.78
      95 1682.94   107.3 1682.19   137.3 1678.52   187.2    1674   202.6 1673.94
     221  1672.3   237.6 1673.27   254.8 1671.63   265.5 1671.92   276.6 1669.84
   302.3 1669.35  305.651669.842   315.2 1672.19   319.5 1672.69   328.2 1671.71
   345.4 1671.92     367 1676.89   375.6 1677.58   401.5 1681.54   431.7 1688.79
   444.6 1693.42   457.7 1694.98   466.2 1698.93   487.8 1705.76   521.9 1714.06
#Mann= 3 ,-1,0
       0      .1       0   276.6    .045       0  305.65      .1       0
Bank Sta=276.6,305.65
XS Rating Curve= 0 ,0
Exp/Cntr(USF)=0,0
Exp/Cntr=0.3,0.1

Type RM Length L Ch R = 1 ,5614    ,156.1,150.4,135.5
XS GIS Cut Line= 2
2213245.36136907725941.340339732 2213638.6574625725775.835648828
#Sta/Elev= 30
       0 1683.34     7.4 1681.56    16.1 1678.26    24.8 1677.55    31.4    1676
    37.8  1673.2    51.1 1662.97    55.1 1660.69    59.5 1659.47    63.8 1659.26
    81.7 1660.22    94.2  1659.7   103.5 1662.29   120.2 1665.31   151.9 1667.97
     181 1669.19   189.7 1668.12   200.8 1663.42     210 1661.36   228.7 1660.89
   233.1 1661.44   240.5 1665.67   243.6  1666.7   298.2 1672.94   329.1 1679.88
   337.2 1682.65     351 1686.11   365.7 1687.14   374.9  1689.9   426.7 1702.27
#Mann= 3 ,-1,0
       0      .1       0     210    .045       0   233.1      .1       0
#XS Ineff= 2 , 0
          122.66 1672.34
Permanent Ineff=
       F       F
Bank Sta=210,233.1
XS Rating Curve= 0 ,0
Exp/Cntr(USF)=0,0
Exp/Cntr=0.3,0.1

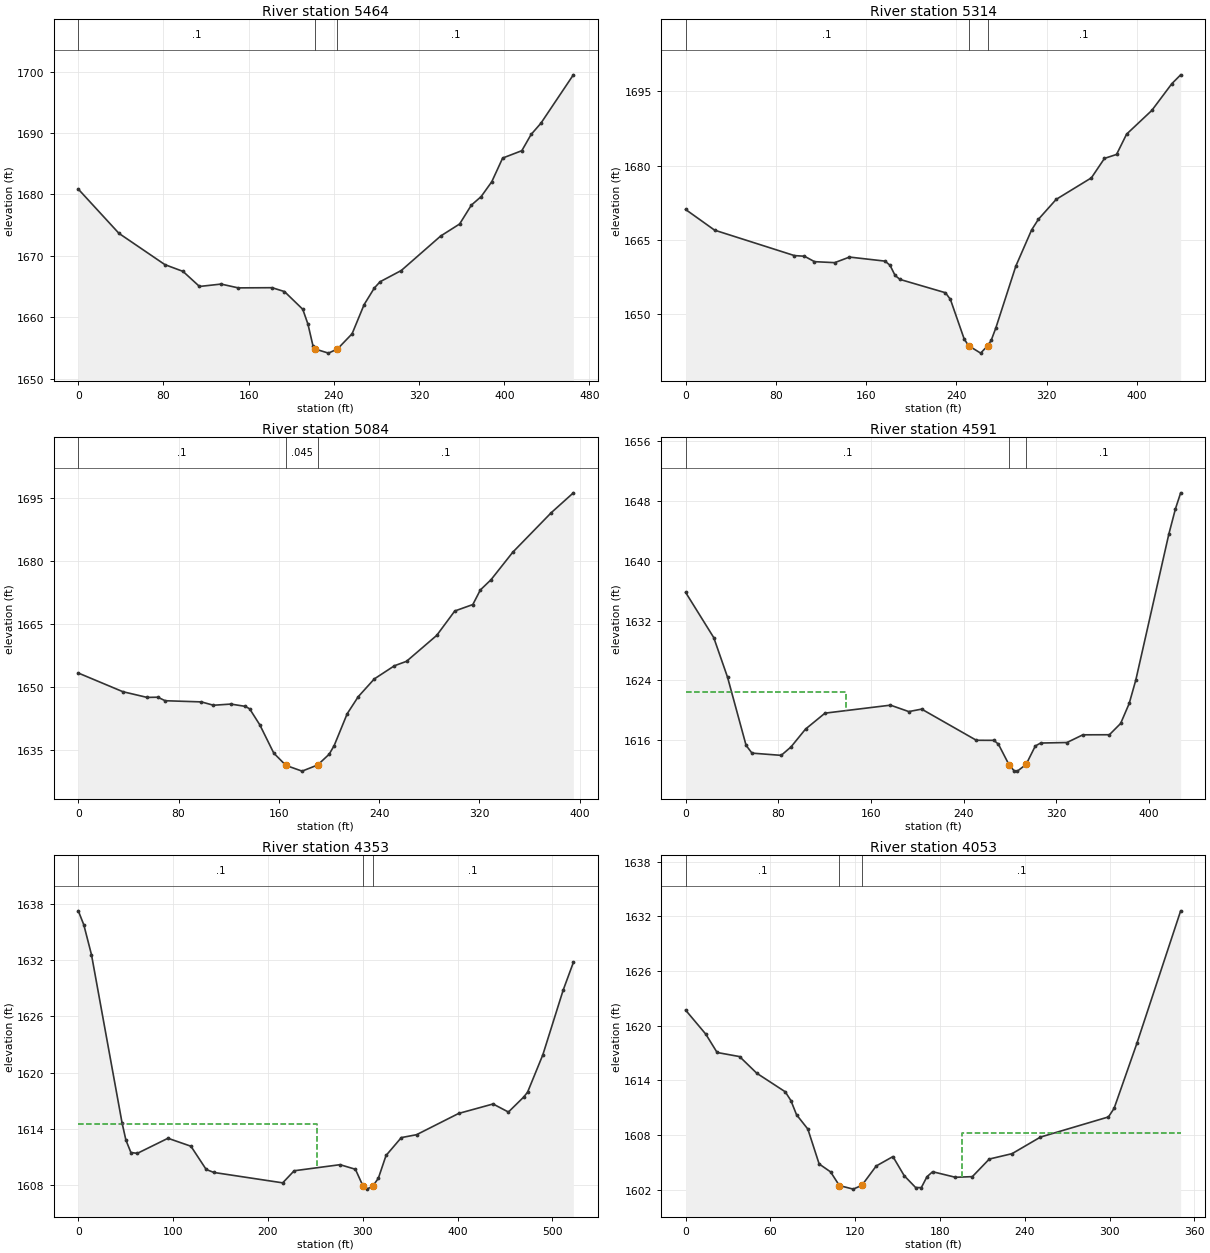
Type RM Length L Ch R = 1 ,5464    ,142.5,150.3,155.2
XS GIS Cut Line= 4
2213315.92234887726072.9391042722213452.17383809726049.881159943
2213594.71385757725833.9749539562213655.50298353725803.580390977
#Sta/Elev= 30
       0 1680.86    38.2 1673.65    81.4 1668.55    98.3 1667.46   113.8    1665
   134.1 1665.39   150.2 1664.77     182  1664.8   193.6 1664.17   210.8 1661.28
   215.7 1658.84   220.5 1655.24   222.4 1654.81   234.9 1654.14  243.371654.814
   257.1 1657.29   268.4 1662.04     278 1664.75   283.4 1665.77   303.3  1667.6
   340.3 1673.22   358.1 1675.18   369.1 1678.25   378.3 1679.64   388.3 1682.07
   398.5 1685.92   416.5 1687.12   425.2 1689.76   434.4 1691.59   464.9 1699.48
#Mann= 3 ,-1,0
       0      .1       0   222.4    .045       0  243.37      .1       0
Bank Sta=222.4,243.37
XS Rating Curve= 0 ,0
Exp/Cntr(USF)=0,0
Exp/Cntr=0.3,0.1

Type RM Length L Ch R = 1 ,5314    ,232.8,229.2,213.3
XS GIS Cut Line= 2
2213401.70297284726137.1549902482213795.18717215725943.331912845
#Sta/Elev= 30
       0 1671.11    25.7 1666.92    96.4 1661.77   105.3 1661.64   114.2 1660.54
   132.1 1660.34   145.2 1661.47   176.7 1660.65   181.1 1659.81   185.6 1657.75
     190 1656.94   230.2 1654.25   234.6  1652.9   246.8 1644.89  250.681643.532
   261.4 1642.02   267.7 1643.54   270.7 1644.59   274.8 1647.08   292.6 1659.66
   306.5 1666.94   312.5  1669.1   328.3 1673.15   359.5 1677.51   371.1 1681.45
   381.8 1682.25   390.7 1686.36     413 1691.15   430.8 1696.58   438.6 1698.37
#Mann= 3 ,-1,0
       0      .1       0  250.68    .045       0   267.7      .1       0
Bank Sta=250.68,267.7
XS Rating Curve= 0 ,0
Exp/Cntr(USF)=0,0
Exp/Cntr=0.3,0.1

Type RM Length L Ch R = 1 ,5084    ,486.1,493.3,496.4
XS GIS Cut Line= 2
2213640.95341001726338.8030977992213860.43991766726010.562014287
#Sta/Elev= 30
       0  1653.3    35.6 1648.84    54.9 1647.48    63.4 1647.53    69.3 1646.69
    98.2 1646.41   107.8 1645.61   121.7 1645.89   133.3 1645.34   136.7 1644.75
   144.8 1640.93   155.9  1634.2   165.6 1631.26   178.5 1629.89   190.9 1631.35
   200.1 1633.92   204.1 1635.98   214.5 1643.59   223.3 1647.65   236.1 1651.89
   252.2 1655.04   261.8 1656.09   285.9 1662.28   300.3  1668.1   314.7 1669.64
   320.7 1673.12   329.2 1675.56   346.6 1682.14   377.3 1691.57   394.9  1696.3
#Mann= 3 ,-1,0
       0      .1       0   165.6    .045       0   190.9      .1       0
Bank Sta=165.6,190.9
XS Rating Curve= 0 ,0
Exp/Cntr(USF)=0,0
Exp/Cntr=0.3,0.1

Type RM Length L Ch R = 1 ,4591    ,234.2,238.1,242
XS GIS Cut Line= 4
2213801.68225662726557.2188897652213974.63731656726501.428513323
2214129.72919836726417.2155924522214171.78287034726362.499588414
#Sta/Elev= 30
       0 1635.78    24.3 1629.72    36.2 1624.42    52.2  1615.3    57.3 1614.26
    82.5 1613.96    90.9 1615.08   103.5 1617.48   120.3 1619.61   176.8 1620.68
   192.6 1619.82   203.7 1620.15   250.9 1615.98   266.1 1615.97     270 1615.44
     279 1612.73   283.6 1611.87   286.3 1611.85   293.8 1612.74   301.8 1615.22
   306.4 1615.61   329.1 1615.68   342.8 1616.71   365.7 1616.72   375.4 1618.23
   382.8 1620.91   388.5 1624.05     417 1643.58   422.7 1646.96   427.2  1649.1
#Mann= 3 ,-1,0
       0      .1       0     279    .045       0   293.8      .1       0
#XS Ineff= 2 , 0
          138.03 1622.43
Permanent Ineff=
       F       F
Bank Sta=279,293.8
XS Rating Curve= 0 ,0
Exp/Cntr(USF)=0,0
Exp/Cntr=0.3,0.1

Type RM Length L Ch R = 1 ,4353    ,301.6,299.9,300.3
XS GIS Cut Line= 2
2213854.44075161726709.7969892322214372.08069729726641.037798453
#Sta/Elev= 30
       0 1637.28     5.8 1635.79    13.9  1632.6    46.1 1614.68    50.2 1612.81
    55.5 1611.48    62.3 1611.39    94.6    1613   118.8 1612.15   134.9 1609.67
     143 1609.35   215.6 1608.24   227.7 1609.53   276.1 1610.18   292.3 1609.69
   300.3  1607.9   304.4 1607.57  310.711607.902   316.5 1608.73   324.6 1611.16
   340.7 1613.07   356.8 1613.38   401.2 1615.65   437.5 1616.66   453.7  1615.8
   469.8  1617.4   473.9 1617.92     490 1621.91   511.5 1628.83   522.2 1631.77
#Mann= 3 ,-1,0
       0      .1       0   300.3    .045       0  310.71      .1       0
#XS Ineff= 2 , 0
          252.06 1614.57
Permanent Ineff=
       F       F
Bank Sta=300.3,310.71
XS Rating Curve= 0 ,0
Exp/Cntr(USF)=0,0
Exp/Cntr=0.3,0.1

Type RM Length L Ch R = 1 ,4053    ,396.8,404.1,400.7
XS GIS Cut Line= 2
2213973.95649389726948.4921255412214323.11800308726919.662276158
#Sta/Elev= 30
       0 1621.72    14.3 1619.08    22.3 1617.07    38.2 1616.62    50.4 1614.79
    70.5 1612.76    74.5  1611.8    78.5 1610.24    86.5 1608.67    94.5 1604.84
   102.6 1603.97  108.791602.473   118.6 1602.08  124.711602.493   134.9 1604.62
   146.7 1605.65   154.7 1603.55   162.8 1602.25   166.8 1602.25   170.8 1603.44
   174.8 1603.99   190.9 1603.38   202.9 1603.45   214.9 1605.38     231 1605.97
   251.1 1607.79   299.2    1610   303.2 1610.94   319.3 1618.06   350.3 1632.61
#Mann= 3 ,-1,0
       0      .1       0  108.79    .045       0  124.71      .1       0
#XS Ineff= 2 , 0
                           195.5         1608.26
Permanent Ineff=
       F       F
Bank Sta=108.79,124.71
XS Rating Curve= 0 ,0
Exp/Cntr(USF)=0,0
Exp/Cntr=0.3,0.1

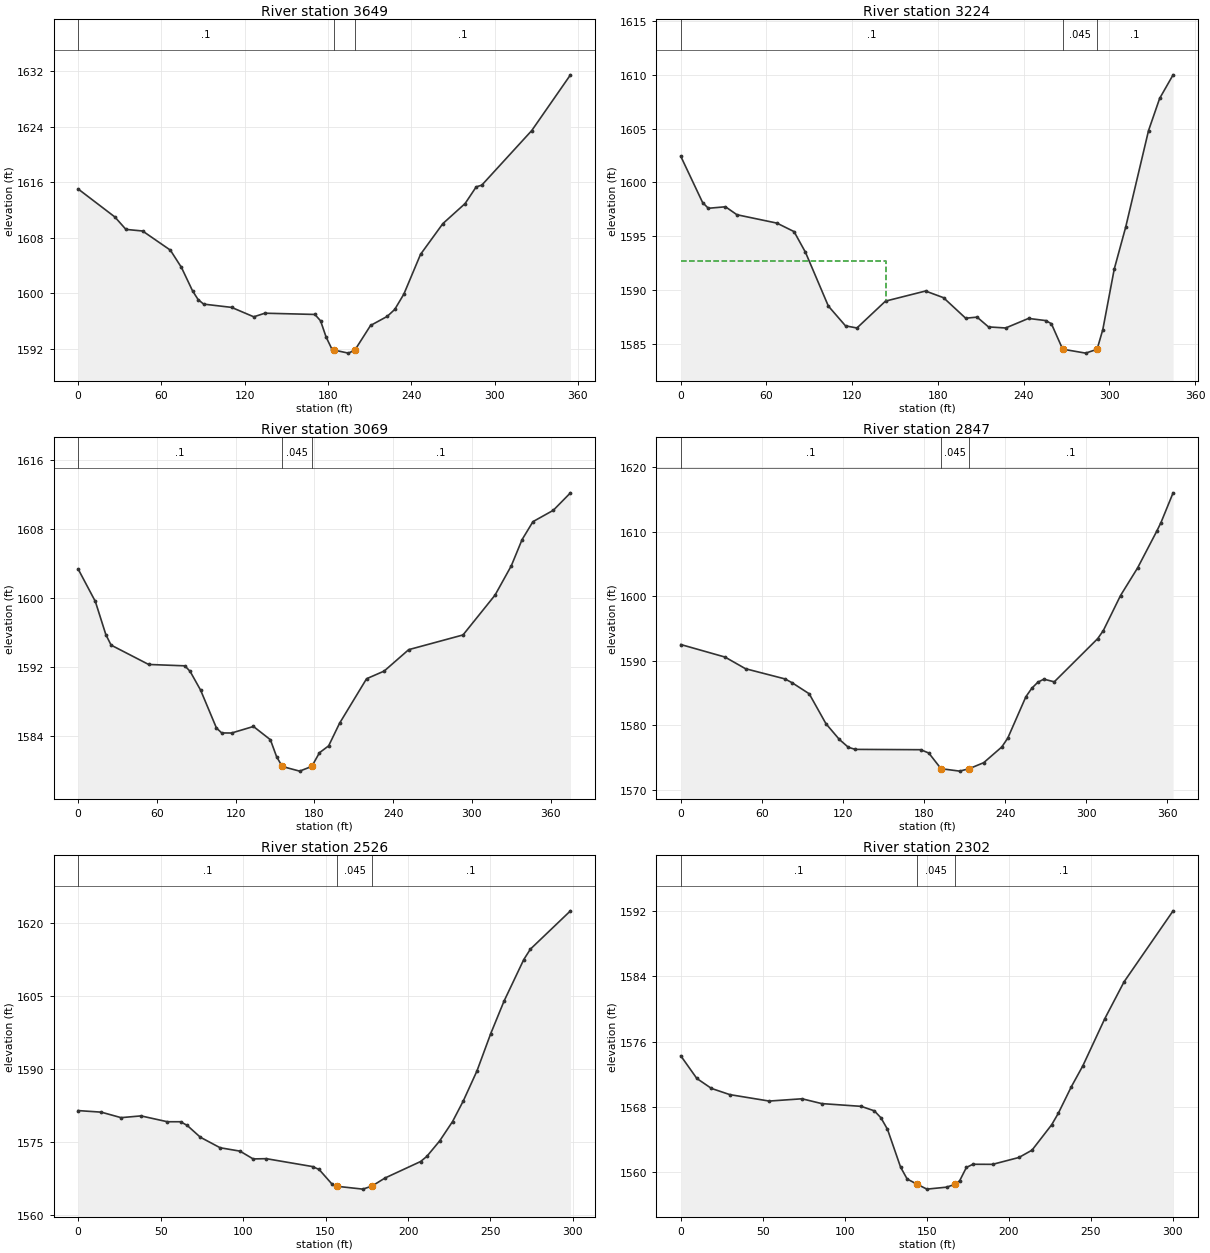
Type RM Length L Ch R = 1 ,3649    ,417.4,425,425.1
XS GIS Cut Line= 2
2213985.84336112727282.0268953772214339.97914049727264.162479206
#Sta/Elev= 30
       0 1615.02    26.4 1610.99    34.4 1609.19    46.4 1608.96    66.4  1606.2
    74.4  1603.7    82.4 1600.32    86.4 1599.07    90.4 1598.41   110.5 1597.94
   126.5 1596.58   134.5  1597.1   170.5 1596.92   174.6    1596   178.6 1593.65
   182.6 1591.99  184.421591.778   194.6 1591.34  199.281591.771   210.6 1595.33
   222.6 1596.64     228 1597.64   234.6 1599.86   246.6 1605.59   262.7 1610.03
   278.7 1612.92   286.7 1615.33   290.7 1615.57   326.7 1623.45   354.6 1631.49
#Mann= 3 ,-1,0
       0      .1       0  184.42    .045       0  199.28      .1       0
Bank Sta=184.42,199.28
XS Rating Curve= 0 ,0
Exp/Cntr(USF)=0,0
Exp/Cntr=0.3,0.1

Type RM Length L Ch R = 1 ,3224    ,146.9,155.2,164
XS GIS Cut Line= 2
2214060.90532645727595.3213491212214405.31816705727605.253938565
#Sta/Elev= 30
       0 1602.43    15.3 1598.12    19.3 1597.59    31.3 1597.73    39.3 1596.99
    67.3 1596.21    79.3 1595.42    87.3 1593.49   103.3 1588.49   115.3 1586.65
   123.3 1586.45   143.3 1588.95   171.3 1589.89   183.9 1589.27   199.4 1587.36
   207.4 1587.46   215.4 1586.55   227.4 1586.45   243.4 1587.34   255.4 1587.14
   259.4 1586.85  267.311584.477   283.4 1584.11   291.4 1584.47   295.4  1586.3
   303.4 1591.93   311.4 1595.83   327.4 1604.82   335.2 1607.82   344.6 1610.01
#Mann= 3 ,-1,0
       0      .1       0  267.31    .045       0   291.4      .1       0
#XS Ineff= 2 , 0
          143.62 1592.66
Permanent Ineff=
       F       F
Bank Sta=267.31,291.4
XS Rating Curve= 0 ,0
Exp/Cntr(USF)=0,0
Exp/Cntr=0.3,0.1

Type RM Length L Ch R = 1 ,3069    ,248.2,221.9,203.4
XS GIS Cut Line= 5
2214063.13157686727661.9698697762214194.71202874727651.463445861
2214251.24659552727677.4793526972214319.78850392727688.486082512
2214427.85457847727660.969257974
#Sta/Elev= 30
       0 1603.36    13.1 1599.59    21.1 1595.74    25.1 1594.52    53.7 1592.27
    81.3 1592.11    85.3 1591.47    93.3 1589.29   105.4 1584.88   109.4 1584.31
   116.9  1584.3   133.6 1585.06   146.5 1583.52   151.2 1581.56   155.5 1580.41
   168.8 1579.87  178.05 1580.42   183.9 1582.01   190.9 1582.81   199.2 1585.43
   219.8 1590.61   233.2  1591.5   251.9 1593.99   293.3  1595.7   317.7 1600.33
   330.1 1603.74   338.3 1606.78   346.6 1608.87   362.1 1610.19   375.2 1612.22
#Mann= 3 ,-1,0
       0      .1       0   155.5    .045       0  178.05      .1       0
Bank Sta=155.5,178.05
XS Rating Curve= 0 ,0
Exp/Cntr(USF)=0,0
Exp/Cntr=0.3,0.1

Type RM Length L Ch R = 1 ,2847    ,297.4,320.1,333.5
XS GIS Cut Line= 4
2214204.73160698727904.8148130582214336.08760823727868.035132707
2214397.03679281727742.9842195152214481.10463361727714.611323245
#Sta/Elev= 30
       0 1592.53    32.7 1590.59    47.9 1588.78    77.1  1587.2    82.5 1586.59
      95  1584.9   107.4 1580.26   117.3 1577.82     124  1576.6   129.1 1576.28
   177.5 1576.23   183.5 1575.71   192.5 1573.29   206.3 1572.91   213.4 1573.29
   224.1 1574.22   237.5 1576.66   241.9 1578.03   255.3 1584.44   259.7 1585.76
   264.2  1586.7   268.6 1587.16   276.3 1586.75   308.4 1593.44   312.6  1594.7
   325.3 1600.12   337.9 1604.39     352 1610.05   355.2 1611.42   364.2 1616.04
#Mann= 3 ,-1,0
       0      .1       0   192.5    .045       0   213.4      .1       0
Bank Sta=192.5,213.4
XS Rating Curve= 0 ,0
Exp/Cntr(USF)=0,0
Exp/Cntr=0.3,0.1

Type RM Length L Ch R = 1 ,2526    ,224.2,224.6,224.6
XS GIS Cut Line= 2
2214246.14230434728053.4394847782214544.53124546728062.520887334
#Sta/Elev= 30
       0 1581.44      14 1581.12      26 1579.99    38.1 1580.35    54.1 1579.15
    62.1 1579.15    66.1  1578.4    74.1 1575.97    86.1 1573.81    98.1 1573.12
   106.1 1571.52   114.1 1571.57   142.1 1569.95   146.1 1569.35   154.1 1566.28
  156.961565.901   172.6 1565.32   178.1 1565.94   186.1 1567.61   207.6 1570.98
   211.4 1572.04   219.2 1575.22     227 1579.19   233.5 1583.42   241.8 1589.58
   250.1  1597.2   258.2  1603.9   270.2 1612.45   274.2 1614.58   298.5 1622.44
#Mann= 3 ,-1,0
       0      .1       0  156.96    .045       0   178.1      .1       0
Bank Sta=156.96,178.1
XS Rating Curve= 0 ,0
Exp/Cntr(USF)=0,0
Exp/Cntr=0.3,0.1

Type RM Length L Ch R = 1 ,2302    ,243.1,239.3,233.2
XS GIS Cut Line= 2
2214238.35824501728271.3931461152214538.04452934728286.961264782
#Sta/Elev= 30
       0 1574.27     9.8 1571.49    18.7 1570.27    29.9 1569.51    53.9 1568.72
    73.9    1569    85.9 1568.41     110 1568.07     118 1567.52     122 1566.67
     126 1565.26     134 1560.61     138 1559.16  144.211558.507     150 1557.92
     162 1558.16   167.2 1558.51     170 1558.95   174.1 1560.58   178.1 1560.97
   190.1 1560.96   206.1  1561.8   214.1  1562.7   226.1 1565.82   230.1 1567.21
   238.1 1570.49   245.1 1573.05   258.5 1578.84   270.2 1583.34   300.1 1592.05
#Mann= 3 ,-1,0
       0      .1       0  144.21    .045       0   167.2      .1       0
Bank Sta=144.21,167.2
XS Rating Curve= 0 ,0
Exp/Cntr(USF)=0,0
Exp/Cntr=0.3,0.1

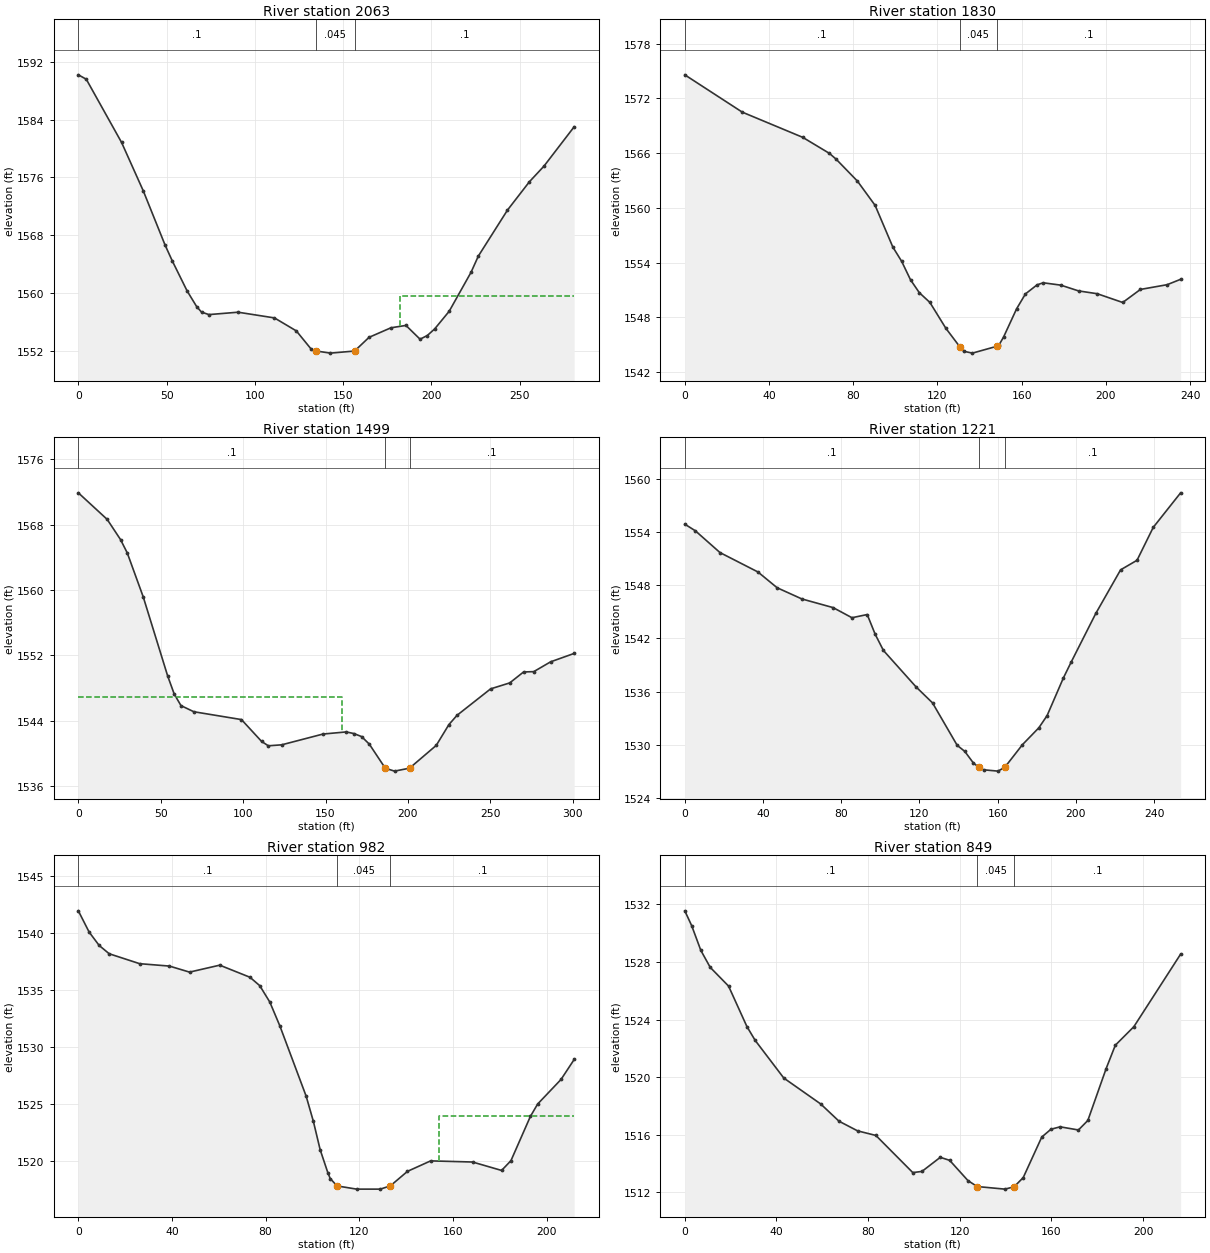
Type RM Length L Ch R = 1 ,2063    ,231.4,232.1,230.3
XS GIS Cut Line= 2
2214300.46888408728546.8963894632214572.75079492728478.025082604
#Sta/Elev= 30
       0 1590.22     4.5 1589.61    24.5 1580.85    36.8 1574.14    49.2  1566.6
    53.3  1564.4    61.6 1560.29      67 1558.12    69.8 1557.34      74    1557
    90.5 1557.33   111.1 1556.54   123.5 1554.74   131.7 1552.28  134.441551.967
   142.8 1551.66   156.5 1551.95   164.7 1553.85   177.1 1555.17   185.6  1555.5
   193.6 1553.59   197.7  1554.1   201.9 1555.02   210.1 1557.46   222.5 1562.87
   226.6  1565.1   243.1 1571.47   255.5 1575.39   263.8 1577.57   280.9 1583.02
#Mann= 3 ,-1,0
       0      .1       0  134.44    .045       0   156.5      .1       0
#XS Ineff= 2 , 0
                          182.18         1559.57
Permanent Ineff=
       F       F
Bank Sta=134.44,156.5
XS Rating Curve= 0 ,0
Exp/Cntr(USF)=0,0
Exp/Cntr=0.3,0.1

Type RM Length L Ch R = 1 ,1830    ,333.9,331.7,327.6
XS GIS Cut Line= 2
2214342.11199985728777.5351845292214566.34416172728705.460561071
#Sta/Elev= 30
       0 1574.57    27.3 1570.48      56 1567.72    68.7 1565.96    71.9 1565.32
      82 1562.92    90.4 1560.26    98.8  1555.7     103 1554.13   107.2 1552.11
   111.4 1550.69   116.4 1549.63     124 1546.79  130.561544.783   132.4 1544.28
   136.6 1544.07   148.2 1544.82   149.2 1544.95   151.4 1545.83   157.6 1548.93
   161.8 1550.56   167.3 1551.55   170.2 1551.78   178.6 1551.52     187 1550.89
   195.9 1550.58     208 1549.62   216.4 1551.05   229.1 1551.57   235.5 1552.16
#Mann= 3 ,-1,0
       0      .1       0  130.56    .045       0   148.2      .1       0
Bank Sta=130.56,148.2
XS Rating Curve= 0 ,0
Exp/Cntr(USF)=0,0
Exp/Cntr=0.3,0.1

Type RM Length L Ch R = 1 ,1499    ,268.9,277.9,289
XS GIS Cut Line= 3
 2214426.9998897 729032.198854082214567.78553699729059.433159916
2214702.48511714728977.742471912
#Sta/Elev= 30
       0 1571.91    17.5 1568.66    25.6 1566.19    29.7 1564.55    39.4 1559.16
    54.2  1549.5    58.2 1547.27    62.3 1545.86    70.1 1545.11      99 1544.15
   111.2 1541.48   115.3 1540.94   123.4 1541.06   148.5 1542.38   162.6 1542.64
   167.2 1542.44   171.9 1542.07   176.6 1541.14   186.3 1538.19   191.9 1537.84
     2011538.202   217.2 1540.99   224.9 1543.54   229.8 1544.67   250.2 1547.91
   261.8 1548.64   270.2 1549.98   276.4 1550.02   286.6 1551.22   300.9 1552.25
#Mann= 3 ,-1,0
       0      .1       0   186.3    .045       0     201      .1       0
#XS Ineff= 2 , 0
          160.18 1546.91
Permanent Ineff=
       F       F
Bank Sta=186.3,201
XS Rating Curve= 0 ,0
Exp/Cntr(USF)=0,0
Exp/Cntr=0.3,0.1

Type RM Length L Ch R = 1 ,1221    ,236.5,238.4,237.3
XS GIS Cut Line= 2
2214418.99159821729235.6094580622214661.48666883729309.684232403
#Sta/Elev= 30
       0 1554.91     5.4 1554.16      18  1551.7    37.4 1549.51    47.2 1547.73
    59.9 1546.46    75.9 1545.48    85.5 1544.34    93.3  1544.7    97.4 1542.46
   101.6 1540.64   118.3 1536.52   126.7 1534.72   139.3 1529.93   143.2 1529.24
   147.6 1527.93  150.361527.448   152.8 1527.16   160.2 1527.01  163.691527.447
   172.7    1530   181.1 1531.91   185.3 1533.28   193.6 1537.52   197.6 1539.32
   210.2 1544.82   222.9 1549.75   231.3 1550.83   239.6 1554.55   253.6 1558.45
#Mann= 3 ,-1,0
       0      .1       0  150.36    .045       0  163.69      .1       0
Bank Sta=150.36,163.69
XS Rating Curve= 0 ,0
Exp/Cntr(USF)=0,0
Exp/Cntr=0.3,0.1

Type RM Length L Ch R = 1 ,982     ,139,133.6,124.4
XS GIS Cut Line= 2
2214383.86589699729455.6130996512214581.40375388 729532.13677394
#Sta/Elev= 30
       0 1541.98     4.6 1540.12     8.9 1538.94    13.2 1538.21    26.2 1537.34
    38.9 1537.13    47.5  1536.6    60.4 1537.21    73.3 1536.15    77.5 1535.41
    81.8 1533.97    86.1 1531.87    97.3 1525.72   100.4  1523.5   103.3 1521.01
   106.6 1518.98   107.6 1518.48   110.51517.832   118.9 1517.55     129 1517.55
   133.3 1517.84   140.6 1519.11   150.5 1520.03   168.4 1519.93   180.8 1519.19
   184.8 1520.05   193.1 1523.93   196.2 1525.02   206.2 1527.18   211.8 1528.93
#Mann= 3 ,-1,0
       0      .1       0   110.5    .045       0   133.3      .1       0
#XS Ineff= 2 , 0
                          154.02         1523.94
Permanent Ineff=
       F       F
Bank Sta=110.5,133.3
XS Rating Curve= 0 ,0
Exp/Cntr(USF)=0,0
Exp/Cntr=0.3,0.1

Type RM Length L Ch R = 1 ,849     ,222,232.9,235.5
XS GIS Cut Line= 2
2214357.17159201 729640.693614212214572.50565222729619.338170222
#Sta/Elev= 30
       0 1531.56       3 1530.53       7 1528.81    11.1 1527.63    19.1 1526.33
    27.1 1523.52    30.7 1522.56    43.2 1519.94    59.3 1518.14    67.3 1516.94
    75.4 1516.27    83.4 1515.95    99.5 1513.37   103.5 1513.45   111.5 1514.43
   115.6 1514.22   123.6 1512.81   127.6  1512.4   139.7 1512.22   143.7 1512.38
   147.7 1513.02   155.8 1515.84   159.8 1516.38   163.8 1516.55   171.8 1516.33
   175.9 1516.99   183.9  1520.6   187.9 1522.22     196 1523.51   216.4 1528.55
#Mann= 3 ,-1,0
       0      .1       0   127.6    .045       0   143.7      .1       0
Bank Sta=127.6,143.7
XS Rating Curve= 0 ,0
Exp/Cntr(USF)=0,0
Exp/Cntr=0.3,0.1

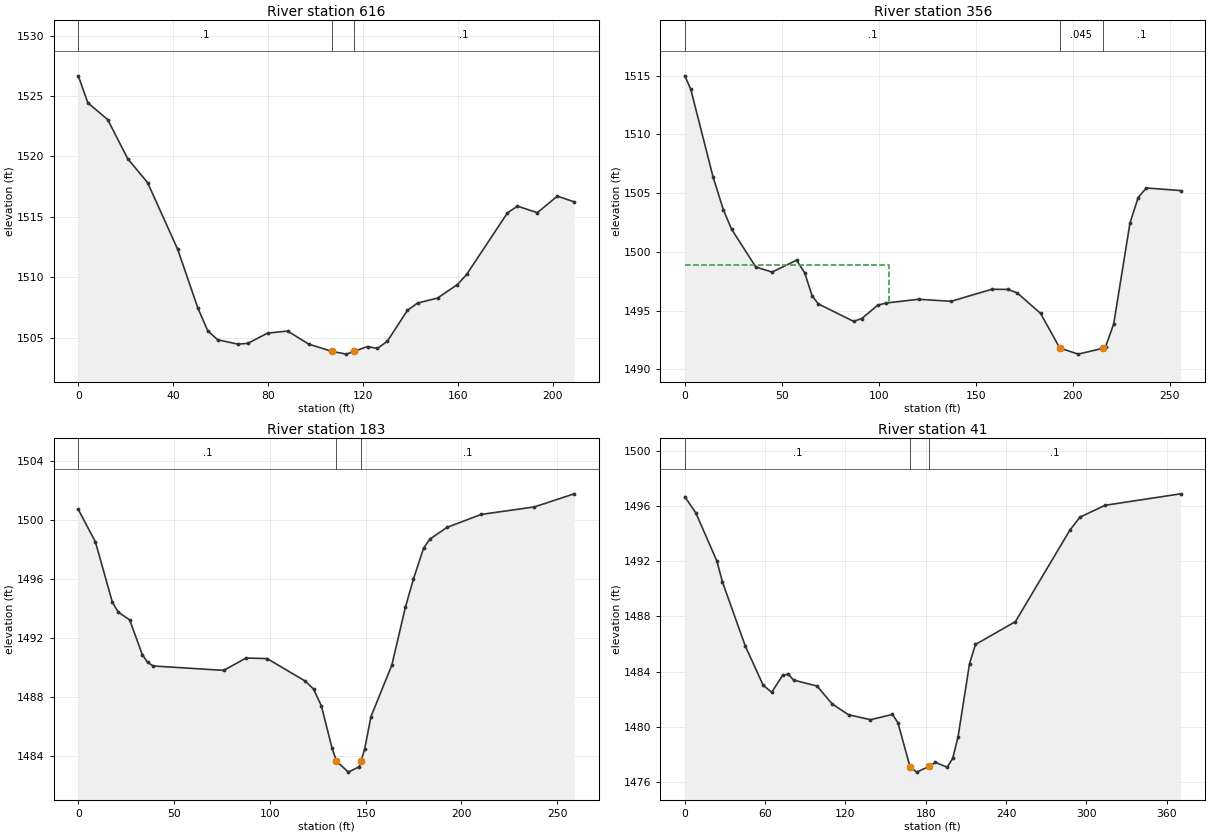
Type RM Length L Ch R = 1 ,616     ,256.4,259.7,261.2
XS GIS Cut Line= 2
2214296.39435435729786.3062429252214494.88786735729851.692341326
#Sta/Elev= 30
       0 1526.67       4 1524.44    12.4 1523.04    20.8 1519.81    29.2 1517.83
    41.9  1512.3    50.3 1507.49    54.5 1505.58    58.7 1504.82    67.2 1504.46
    71.4 1504.52    79.8 1505.37    88.2 1505.54    97.1 1504.46   106.91503.855
     113 1503.63   116.1 1503.85   121.9 1504.26   126.1  1504.1   130.3 1504.71
   138.7 1507.25     143 1507.86   151.4 1508.27   159.8 1509.39   163.7 1510.23
   180.9 1515.33   185.1 1515.88   193.5 1515.34   201.9 1516.71     209 1516.24
#Mann= 3 ,-1,0
       0      .1       0   106.9    .045       0   116.1      .1       0
Bank Sta=106.9,116.1
XS Rating Curve= 0 ,0
Exp/Cntr(USF)=0,0
Exp/Cntr=0.3,0.1

Type RM Length L Ch R = 1 ,356     ,164.2,173.4,178.2
XS GIS Cut Line= 2
2214197.21314719730005.8677912322214441.11367297730082.411041344
#Sta/Elev= 30
       0 1514.99     3.1 1513.83    14.6 1506.36    19.9 1503.58    24.1 1501.93
    36.6 1498.71      45 1498.28    57.6 1499.29    61.8 1498.22    65.6 1496.27
    68.8 1495.57      87 1494.08    91.2 1494.32    99.5 1495.46   103.7 1495.64
   120.5 1495.96   137.3 1495.79   158.2 1496.81   166.6  1496.8   171.4  1496.5
   183.4 1494.76   193.3 1491.81   202.8 1491.29   215.6 1491.79   216.9 1491.92
   221.1 1493.86   229.5 1502.46   233.7 1504.62   237.9 1505.44   255.6 1505.22
#Mann= 3 ,-1,0
       0      .1       0   193.3    .045       0   215.6      .1       0
#XS Ineff= 2 , 0
          105.28 1498.91
Permanent Ineff=
       F       F
Bank Sta=193.3,215.6
XS Rating Curve= 0 ,0
Exp/Cntr(USF)=0,0
Exp/Cntr=0.3,0.1

Type RM Length L Ch R = 1 ,183     ,142.3,142.3,142.3
XS GIS Cut Line= 3
2214178.91690125730099.2723494732214313.27594601730219.540403718
2214383.84653925730185.024385265
#Sta/Elev= 30
       0 1500.72     8.9 1498.52    17.8 1494.41    20.9 1493.74    26.8 1493.22
    33.4 1490.86    36.2 1490.33    39.1 1490.09    75.9 1489.79    87.6 1490.63
    98.6 1490.59   118.4 1489.07   122.8 1488.53   126.9 1487.38   132.5  1484.5
   134.8 1483.63     141 1482.88   146.7 1483.25  147.54 1483.61   149.5 1484.44
   152.8 1486.65   163.7 1490.15   170.8 1494.09     175    1496   180.3  1498.1
   183.6 1498.71   192.5  1499.5   210.3 1500.38   238.1 1500.89   258.9 1501.78
#Mann= 3 ,-1,0
       0      .1       0   134.8    .045       0  147.54      .1       0
Bank Sta=134.8,147.54
XS Rating Curve= 0 ,0
Exp/Cntr(USF)=0,0
Exp/Cntr=0.3,0.1

Type RM Length L Ch R = 1 ,41      ,,,
XS GIS Cut Line= 4
2214145.66798598730145.7780936752214180.27633775730301.677429534
2214227.05556584730309.0220004992214375.38129383730240.686734249
#Sta/Elev= 30
       0 1496.68     8.3  1495.5      24 1492.01    28.1 1490.51    45.2 1485.86
    58.6 1483.01    64.9 1482.51    73.1 1483.74    77.2 1483.82    81.3 1483.39
    98.8 1482.96     110 1481.67   122.3 1480.88   138.7 1480.52   155.1  1480.9
   159.2 1480.31168.18831477.121   173.2 1476.72  182.58 1477.14   187.2 1477.42
     196 1477.08   200.1 1477.71   204.1 1479.26   212.7 1484.58   217.1 1485.97
     247 1487.63   287.6 1494.25   295.2  1495.2     314 1496.06   370.4 1496.89
#Mann= 3 ,-1,0
       0      .1       0168.1883    .045       0  182.58      .1       0
Bank Sta=168.1883,182.58
XS Rating Curve= 0 ,0
Exp/Cntr(USF)=0,0
Exp/Cntr=0.3,0.1
LCMann Table=0

Chan Stop Cuts=-1
Use User Specified Reach Order=0
Composite Channel Slope=5